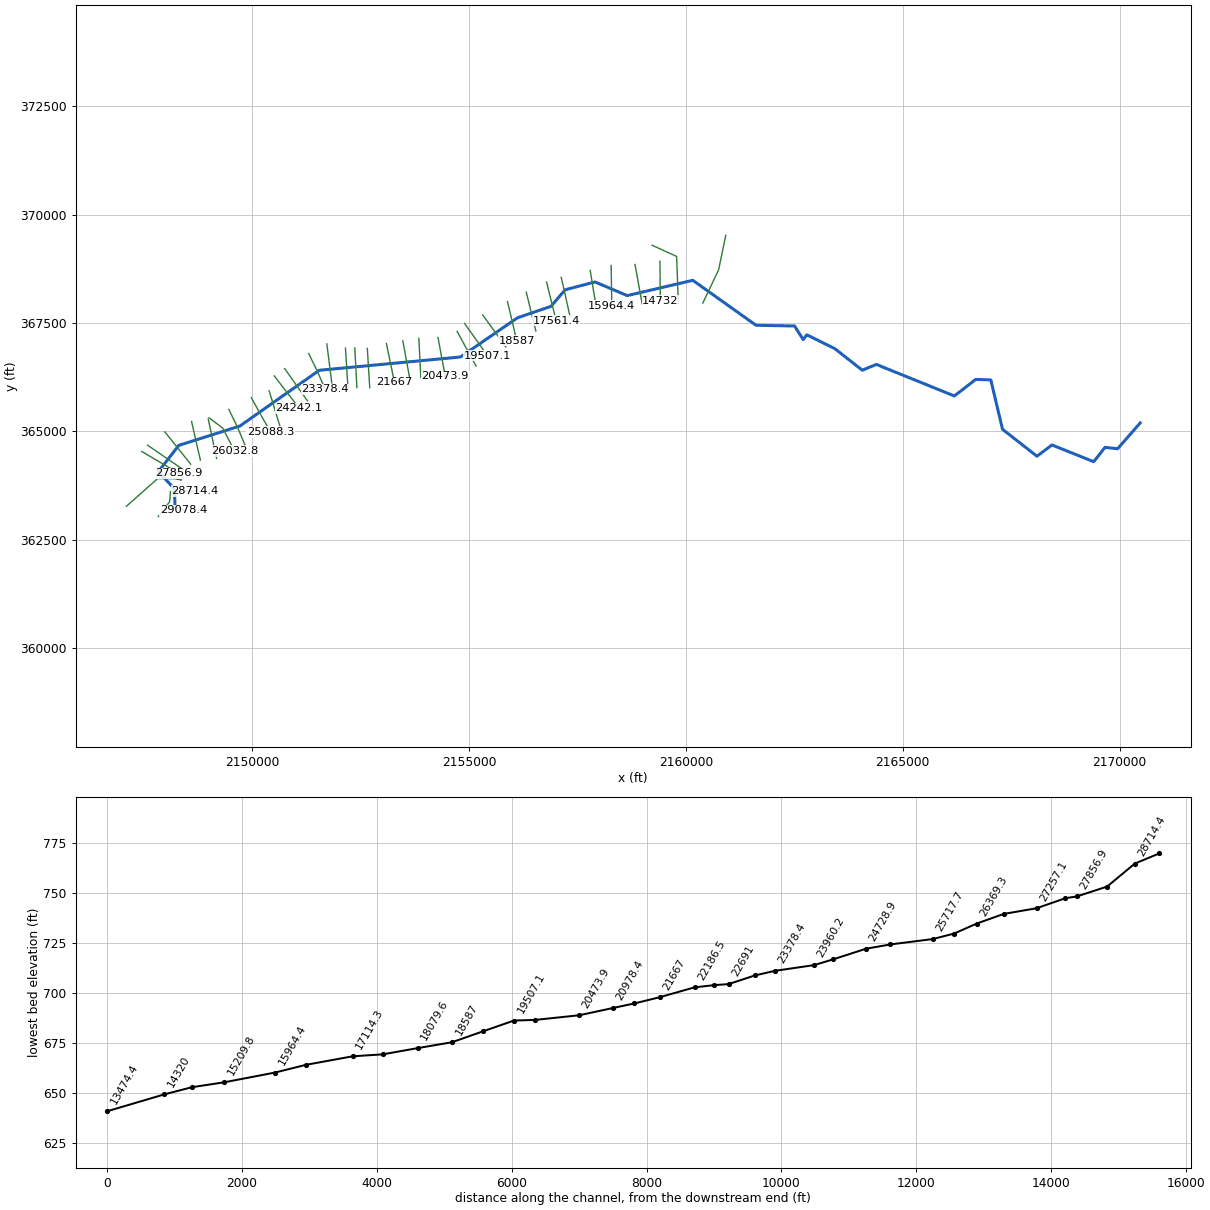
--- HRSSHRN.prj (project) ---

Proj Title=HRSSHRN
Current Plan=p01
Default Exp/Contr=0,0
English Units
Geom File=g01
Flow File=f01
Plan File=p01
BEGIN DESCRIPTION:
END DESCRIPTION:
DSS Export Rating Curves= 0
DSS Export Rating Curve Sorted= 0
DSS Export Volume Flow Curves= 0
DXF OffsetX= 0
DXF OffsetY= 0
DXF ScaleX= 0
DXF ScaleY= 0

--- HRSSHRN.p01 (plan) ---

Plan Title=Floodplain
Program Version=4.00
Geom File=g01
Flow File=f01
K Sum by GR=0
Std Step Tol=0.01
Critical Tol=0.01
Num of Std Step Trials=20
Max Error Tol=0.3
Flow Tol Ratio=0.001
Split Flow NTrial=30
Split Flow Tol=0.02
Split Flow Ratio=0.02
Log Output Level=0
Friction Slope Method=1
Unsteady Friction Slope Method=2
Unsteady Bridges Friction Slope Method=1
Global Log Level=0
CheckData=False
Run HTab=0
Run UNet=0
Run PostProcess=0
UNET Theta=0
UNET Theta Warmup=0
UNET ZTol=0
UNET ZSATol=0
UNET MxIter=0
UNET MaxInSteps=0
UNET DtIC=0
UNET DtMin=0
UNET MaxCRTS=0
UNET WFStab=0
UNET SFStab=0
UNET WFX=0
UNET SFX=0
UNET DSS MLevel=0
UNET DZMax Abort=0
UNET Convert EG Bridges=0
UNET Use Existing IB Tables=0
UNET Froude Limit=0
UNET Froude Power=0
Write IC File=0
Echo Input=False
Echo Output=False
Write Detailed=0

--- HRSSHRN.f01 (steady flow) ---

Flow Title=NFF Regression Equation
Program Version=4.00
Number of Profiles=1
Profile Names=P100yr
River Rch & RM=HRSSHRN,Main      ,29078.4
     110
River Rch & RM=HRSSHRN,Main      ,28304.3
     112
River Rch & RM=HRSSHRN,Main      ,28304.3
     246
River Rch & RM=HRSSHRN,Main      ,27856.9
     250
River Rch & RM=HRSSHRN,Main      ,27684.1
     338
River Rch & RM=HRSSHRN,Main      ,27257.1
     370
River Rch & RM=HRSSHRN,Main      ,25717.7
     386
River Rch & RM=HRSSHRN,Main      ,25088.3
     522
River Rch & RM=HRSSHRN,Main      ,24242.1
     574
River Rch & RM=HRSSHRN,Main      ,23960.2
     659
River Rch & RM=HRSSHRN,Main      ,22691
     671
River Rch & RM=HRSSHRN,Main      ,22478.4
     867
River Rch & RM=HRSSHRN,Main      ,21667
     891
River Rch & RM=HRSSHRN,Main      ,18079.6
     990
River Rch & RM=HRSSHRN,Main      ,16421.4
    1087
River Rch & RM=HRSSHRN,Main      ,15964.4
    1340
River Rch & RM=HRSSHRN,Main      ,13474.4
    1371
River Rch & RM=HRSSHRN,Main      ,13474.4
    1564
River Rch & RM=HRSSHRN,Main      ,11361.3
    1576
River Rch & RM=HRSSHRN,Main      ,11361.3
    1852
River Rch & RM=HRSSHRN,Main      ,5747.1
    2011
Boundary for River Rch & Prof#=HRSSHRN,Main      ,1
Up Type=0
Dn Type=3
Dn Slope=0.003687

--- HRSSHRN.g01 (geometry) ---

Geom Title=USGS 10m DEM
Program Version=4.00

River Reach=HRSSHRN         ,Main
Reach XY= 30
     2148215.402      363241.983     2148206.387      363668.653
     2147832.798      364070.231     2148301.998      364675.372
     2149712.763      365123.225     2151543.304      366409.012
     2154799.434      366715.998     2156114.969      367620.858
     2156885.239      367883.944     2157213.205      368266.552
     2157900.715      368447.902     2158644.726      368132.657
     2160156.495      368485.132     2161615.434      367447.599
     2162504.578      367431.125     2162701.665      367118.412
     2162788.103      367227.031     2163430.963      366908.769
     2164065.954      366410.759     2164390.432      366544.359
     2166188.463      365816.562     2166681.446      366198.588
     2167029.416      366186.613     2167299.006      365048.045
      2168093.91      364425.298     2168439.562      364685.456
     2169402.411       364299.53     2169663.923      364630.747
     2169953.977      364598.244     2170474.121      365193.317

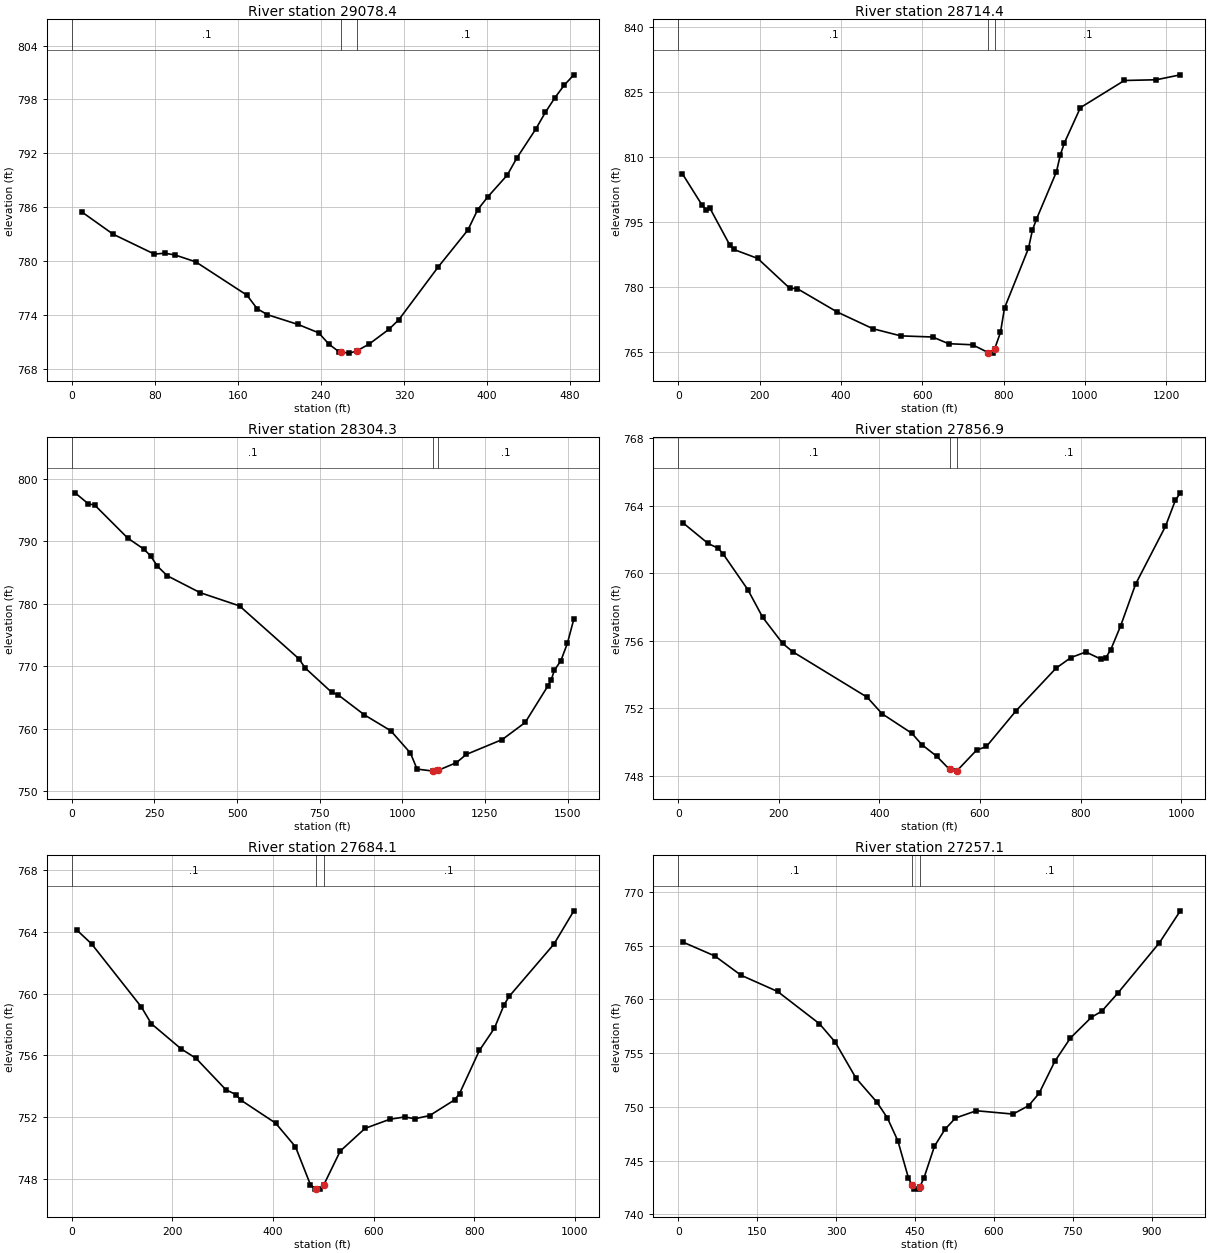
Type RM Length L Ch R = 1 ,29078.4 ,359.8,364,368.6
XS GIS Cut Line= 5
     2147987.138      363195.626     2148059.927      363277.452
      2148215.86      363251.947     2148365.572      363225.231
     2148410.786      363179.847
#Sta/Elev= 30
      10  785.44    39.8  782.99    79.6  780.77    89.6  780.87    99.6  780.67
   119.4  779.91   168.8  776.19   178.6  774.69   188.5  774.02   218.1  772.93
   237.9     772   247.8  770.73   257.6  769.88   259.5  769.85   267.5  769.74
   274.5  769.98   286.5  770.75   305.5  772.39     315  773.45   353.1  779.35
   381.6  783.45   391.1  785.72   400.6  787.12   419.6  789.58   428.8  791.48
   447.1  794.71   456.2  796.55   465.4  798.18   474.5   799.6   483.7  800.74
#Mann= 3 , 0 , 0
       0      .1       0   259.5    .045       0   274.5      .1       0
Bank Sta=259.5,274.5
XS Rating Curve= 0 ,0
Exp/Cntr=0.3,0.1

Type RM Length L Ch R = 1 ,28714.4 ,417.7,410.1,402.6
XS GIS Cut Line= 4
     2147830.678      363035.358     2148092.153      363376.652
      2148111.42      363610.604     2148681.162      363624.366
#Sta/Elev= 30
     9.8  806.19    58.6  798.88    68.4  797.86    78.2  798.12     127  789.61
   136.8  788.62   195.4  786.55   273.6   779.7   293.1  779.54   390.9  774.16
   478.8  770.29   547.3  768.64   625.6  768.38   664.7  766.83   723.6  766.58
   762.9  764.75   772.8  764.65   777.9  765.57   792.4  769.46   802.3  775.08
   861.2  788.88     871  793.11   880.9  795.63     930  806.58   939.8  810.58
   949.6  813.28   988.9  821.42    1097   827.7  1175.6  827.87  1234.6  829.01
#Mann= 3 , 0 , 0
       0      .1       0   762.9    .045       0   777.9      .1       0
Bank Sta=762.9,777.9
XS Rating Curve= 0 ,0
Exp/Cntr=0.3,0.1

Type RM Length L Ch R = 1 ,28304.3 ,452.7,447.3,445.9
XS GIS Cut Line= 4
     2147094.113      363270.354     2147816.439      363910.534
      2148203.47      363907.154     2148367.408      363876.732
#Sta/Elev= 30
      10   797.8    49.8  796.05    69.7  795.82   169.2  790.55   218.9  788.74
   238.8  787.67   258.7  786.06   288.6  784.51   388.1   781.8   507.5  779.67
   686.6  771.22   706.5   769.7   786.1  765.83     806   765.4   885.6  762.19
   965.2  759.65  1024.7  756.07  1044.6  753.51  1093.6  753.18  1108.6  753.31
  1163.7  754.54  1193.4  755.85  1302.6  758.25  1371.8  760.98  1440.5  766.84
  1450.3  767.76  1460.1  769.35  1479.7  770.88  1499.4  773.66    1519  777.56
#Mann= 3 , 0 , 0
       0      .1       0  1093.6    .045       0  1108.6      .1       0
Bank Sta=1093.6,1108.6
XS Rating Curve= 0 ,0
Exp/Cntr=0.3,0.1

Type RM Length L Ch R = 1 ,27856.9 ,185.3,172.8,168.6
XS GIS Cut Line= 2
     2147449.353      364534.112     2148311.158      364030.187
#Sta/Elev= 30
     9.9  762.97    59.3  761.76    79.1  761.48      89  761.15   138.4  759.02
     168  757.38   207.6  755.84   227.3  755.35   375.6  752.65   405.3  751.67
   464.6  750.51   484.3  749.84     514  749.15   539.5  748.37   553.5  748.27
   554.5   748.3   593.1  749.51   612.8  749.73   672.1  751.86   751.2  754.37
   780.9     755   810.5  755.33   840.2  754.91   850.1  754.99   859.9  755.46
   879.7  756.88   909.4  759.35   968.7  762.77   988.4  764.31   998.3  764.76
#Mann= 3 , 0 , 0
       0      .1       0   539.5    .045       0   554.5      .1       0
Bank Sta=539.5,554.5
XS Rating Curve= 0 ,0
Exp/Cntr=0.3,0.1

Type RM Length L Ch R = 1 ,27684.1 ,421.8,427,425.1
XS GIS Cut Line= 2
     2147583.089      364680.814     2148406.113      364115.765
#Sta/Elev= 30
     9.9  764.11    39.5  763.21   138.4  759.13   158.2  758.05   217.5  756.42
   247.1  755.81   306.4  753.78   326.2  753.47   336.1  753.11   405.3  751.62
   444.8  750.09   474.5  747.64   484.3  747.35     486  747.35   494.2  747.36
     501  747.62   533.8  749.81   583.2  751.28   632.6  751.87   662.3  752.02
     682   751.9   711.7  752.11   761.1  753.12     771  753.53   810.5  756.32
   840.2  757.75   859.9  759.29   869.8  759.82   958.8   763.2   998.3  765.35
#Mann= 3 , 0 , 0
       0      .1       0     486    .045       0     501      .1       0
Bank Sta=486,501
XS Rating Curve= 0 ,0
Exp/Cntr=0.3,0.1

Type RM Length L Ch R = 1 ,27257.1 ,497.4,486.6,475.9
XS GIS Cut Line= 2
     2147981.902       364987.75     2148577.656       364242.63
#Sta/Elev= 30
     9.9   765.3    69.6  764.03   119.3  762.24   188.8  760.73   268.3  757.73
   298.1  756.03   337.9  752.66   377.6  750.43   397.5  748.96   417.4  746.83
   437.3  743.41   443.8  742.75   447.2   742.4   457.1  742.35   458.8  742.53
   467.1  743.42   486.9  746.34   506.8  747.91   526.7  748.96   566.4  749.64
     636  749.33   665.8  750.11   685.7  751.26   715.5  754.23   745.3  756.41
   785.1  758.33   804.9   758.9   834.8  760.55   914.3  765.26     954  768.23
#Mann= 3 , 0 , 0
       0      .1       0   443.8    .045       0   458.8      .1       0
Bank Sta=443.8,458.8
XS Rating Curve= 0 ,0
Exp/Cntr=0.3,0.1

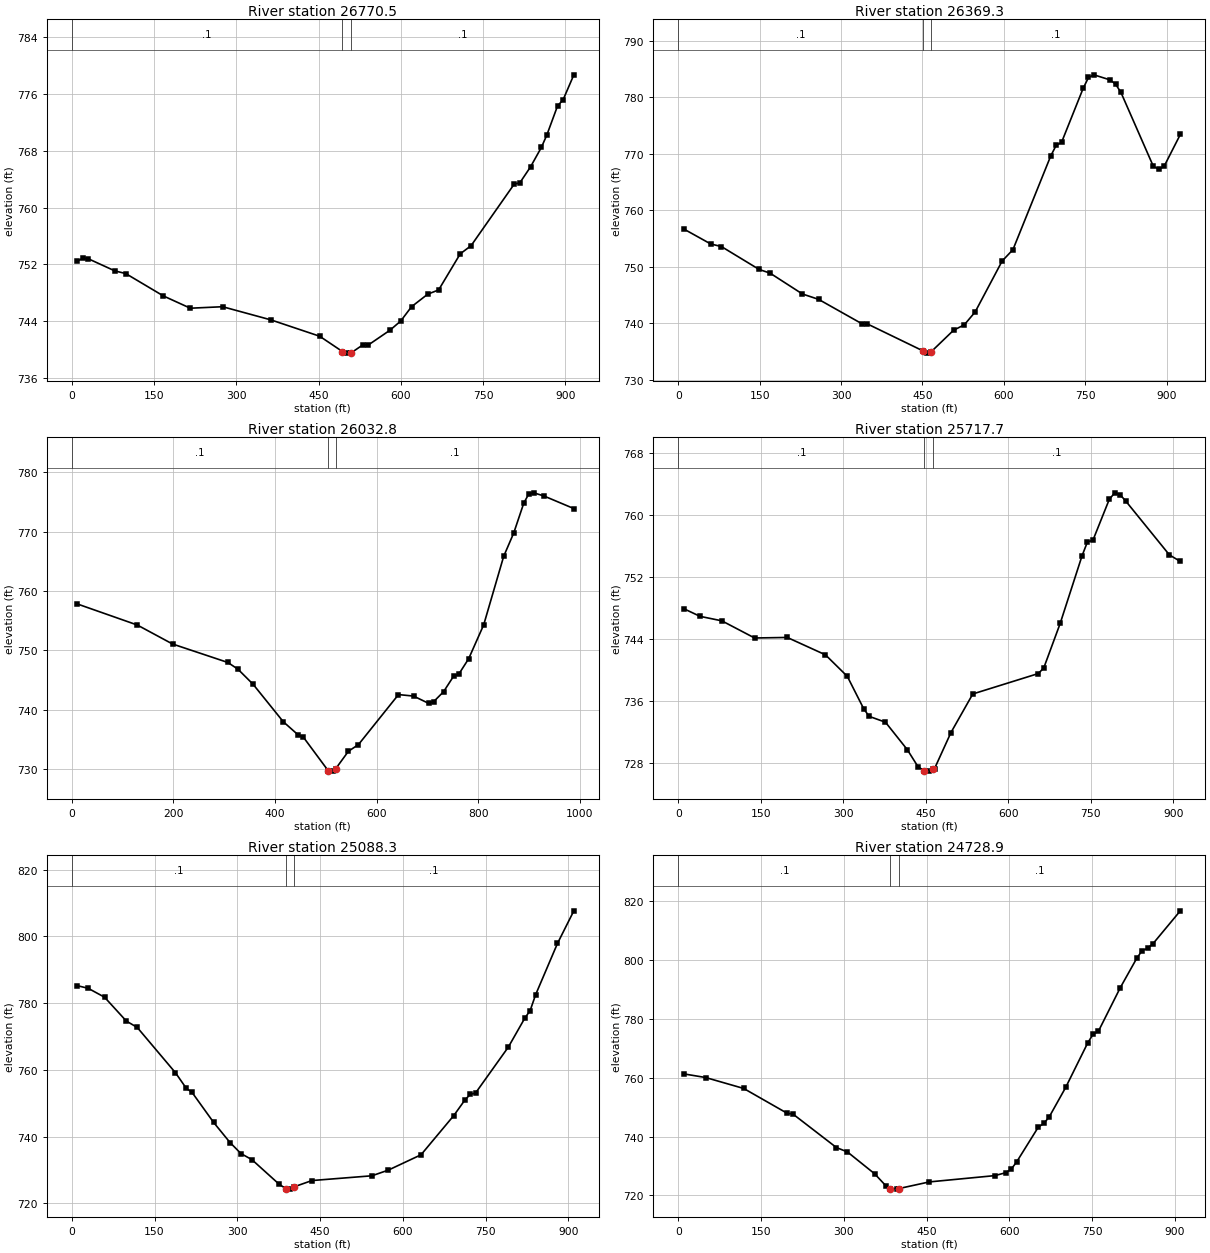
Type RM Length L Ch R = 1 ,26770.5 ,401.9,401.1,400.4
XS GIS Cut Line= 3
     2148598.341        365228.4      2148699.22      364777.761
     2148801.812      364335.708
#Sta/Elev= 30
     9.8  752.44    19.7  752.85    29.5  752.81    78.6  751.08    98.3  750.71
     167  747.56   216.2  745.83   275.1  746.04   363.5  744.18     452  741.89
   493.7  739.73   501.3  739.51   508.7  739.51   530.8  740.67   540.7  740.65
   580.2  742.73   599.9  744.03   619.6  746.04   649.2  747.81     669   748.4
   708.4  753.48   728.2  754.63   807.1  763.32   816.9  763.45   836.7  765.73
   856.4  768.46   866.3  770.19     886  774.32   895.9  775.14   915.6  778.67
#Mann= 3 , 0 , 0
       0      .1       0   493.7    .045       0   508.7      .1       0
Bank Sta=493.7,508.7
XS Rating Curve= 0 ,0
Exp/Cntr=0.3,0.1

Type RM Length L Ch R = 1 ,26369.3 ,329.3,336.5,343.4
XS GIS Cut Line= 2
     2148982.997      365280.338     2149175.202      364375.364
#Sta/Elev= 30
     9.9  756.71    59.7  754.05    79.6  753.58   149.2  749.52   169.1  748.88
   228.8  745.18   258.6  744.23   338.2  739.92   348.2  739.89   451.4  735.08
   457.6   734.7   466.4  734.97   507.3  738.75   527.2  739.72   547.1  741.99
   596.9  751.02   616.8  753.04   686.4  769.63   696.4  771.51   706.3  772.03
   746.1   781.6     756  783.54     766  784.01   795.8  783.11   805.8  782.37
   815.7  780.91   875.4  767.82   885.4  767.28   895.3  767.79   925.2  773.44
#Mann= 3 , 0 , 0
       0      .1       0   451.4    .045       0   466.4      .1       0
Bank Sta=451.4,466.4
XS Rating Curve= 0 ,0
Exp/Cntr=0.3,0.1

Type RM Length L Ch R = 1 ,26032.8 ,315.4,315.1,313.5
XS GIS Cut Line= 3
      2149000.65      365312.897     2149317.875      365074.683
     2149586.304      364547.388
#Sta/Elev= 30
     9.9  757.85   128.9  754.28   198.4  751.08   307.4  747.97   327.3  746.83
     357   744.3   416.4     738     446  735.76   455.9  735.41   504.9  729.75
     515  729.69   519.9  730.13   544.6  733.03   564.4  734.16   643.2  742.57
   672.8  742.32   702.4   741.1   712.3  741.37     732  743.06   751.7  745.67
   761.6  745.97   781.3   748.6   810.9   754.3   850.3  765.84   870.1  769.77
   889.8  774.78   899.6  776.32   909.5  776.52   929.2     776   988.4  773.87
#Mann= 3 , 0 , 0
       0      .1       0   504.9    .045       0   519.9      .1       0
Bank Sta=504.9,519.9
XS Rating Curve= 0 ,0
Exp/Cntr=0.3,0.1

Type RM Length L Ch R = 1 ,25717.7 ,628.3,629.4,631.7
XS GIS Cut Line= 3
     2149458.422      365504.672      2149657.39      365094.411
     2149834.221      364673.452
#Sta/Elev= 30
     9.9  747.89    39.6   746.9    79.3  746.32   138.8  744.11   198.2  744.18
   267.6  741.94   307.3  739.17     337  735.01   346.9  734.02   376.7  733.26
   416.3  729.73   436.1   727.5   447.6     727     456  726.96   462.6  727.18
   465.9  727.29   495.7  731.93   535.4   736.9   654.5  739.53   664.4  740.25
   694.2  745.98   733.9  754.68   743.8  756.49   753.7  756.69   783.5  761.97
   793.4  762.81   803.4  762.55   813.3  761.76   892.7  754.82   912.6  753.97
#Mann= 3 , 0 , 0
       0      .1       0   447.6    .045       0   462.6      .1       0
Bank Sta=447.6,462.6
XS Rating Curve= 0 ,0
Exp/Cntr=0.3,0.1

Type RM Length L Ch R = 1 ,25088.3 ,364,359.4,354.8
XS GIS Cut Line= 3
     2149976.382      365777.927     2150195.158      365378.873
     2150421.067      364983.935
#Sta/Elev= 30
     9.9  785.26    29.7  784.47    59.4   781.8    98.9  774.65   118.7  772.73
     188  759.15   207.8  754.44   217.7  753.34   257.2  744.25   286.9  738.23
   306.7  734.93   326.5  733.11   375.9  725.74   388.7  724.35   395.7  724.27
   403.7     725   435.3  726.84   544.1  728.27   573.8  729.97   633.1  734.57
   692.5  746.33   712.3  750.91   722.1  752.65     732   753.1   791.4  766.86
   821.1  775.49   830.9   777.8   840.8  782.54   880.4  797.91   910.1  807.69
#Mann= 3 , 0 , 0
       0      .1       0   388.7    .045       0   403.7      .1       0
Bank Sta=388.7,403.7
XS Rating Curve= 0 ,0
Exp/Cntr=0.3,0.1

Type RM Length L Ch R = 1 ,24728.9 ,480.9,486.8,469.6
XS GIS Cut Line= 3
     2150387.158      365935.336     2150519.699      365500.069
      2150652.24      365064.802
#Sta/Elev= 30
     9.9  761.31    49.5  760.08   118.7  756.35   197.8  747.88   207.7  747.69
   286.8  736.26   306.6  734.79   356.1  727.33   375.9  723.36   384.4  722.33
   395.7  722.14   399.4  722.31     455  724.59   573.7  726.73   593.5  727.71
   603.4  728.89   613.3  731.37   652.8  743.27   662.7  744.46   672.6  746.76
   702.3  756.73   741.8  771.69   751.7  774.76   761.6  775.82   801.2  790.61
   830.9  800.55   840.8  803.22   850.7  803.97   860.5  805.56     910  816.73
#Mann= 3 , 0 , 0
       0      .1       0   384.4    .045       0   399.4      .1       0
Bank Sta=384.4,399.4
XS Rating Curve= 0 ,0
Exp/Cntr=0.3,0.1

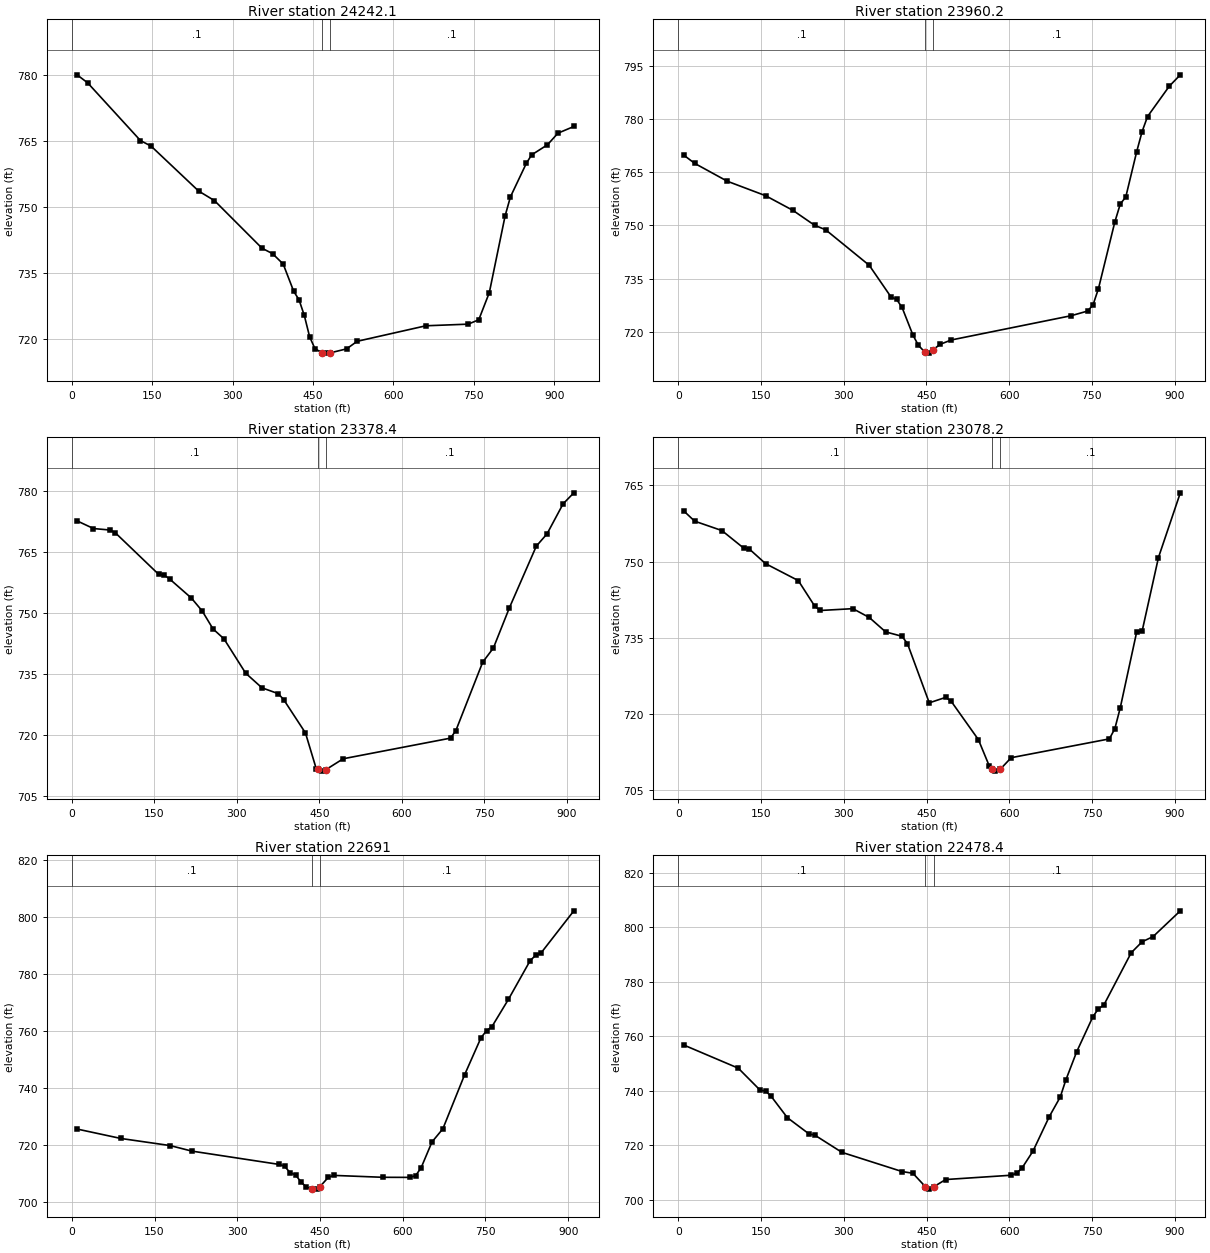
Type RM Length L Ch R = 1 ,24242.1 ,280.8,282,306.2
XS GIS Cut Line= 2
     2150505.202       366278.23     2151077.338      365536.671
#Sta/Elev= 30
     9.9  780.15    29.6  778.33   128.2  765.19   147.9  763.94   236.6  753.72
   266.2  751.54   354.9  740.71   374.6  739.47   394.4  737.11   414.1  730.88
   423.9     729   433.8  725.41   443.7  720.57   453.5   717.9   466.4  716.92
   473.2  716.85   481.4  716.89   512.7  717.82   532.4  719.54   660.6  723.07
   739.4  723.44   759.2  724.43   778.9  730.61   808.4  748.08   818.3  752.39
   847.9     760   857.7  761.93   887.3  764.23     907  766.88   936.6   768.4
#Mann= 3 , 0 , 0
       0      .1       0   466.4    .045       0   481.4      .1       0
Bank Sta=466.4,481.4
XS Rating Curve= 0 ,0
Exp/Cntr=0.3,0.1

Type RM Length L Ch R = 1 ,23960.2 ,585.4,581.7,577.2
XS GIS Cut Line= 2
     2150744.967      366448.364     2151269.529      365704.519
#Sta/Elev= 30
     9.9  769.81    29.7  767.48      89  762.43   158.3  758.36   207.8  754.23
   247.3     750   267.1  748.76   346.3  738.72   385.8  729.78   395.7  729.13
   405.6  726.91   425.4  719.08   435.3  716.18   447.4  714.19   455.1  713.96
   462.4  714.98   474.9  716.44   494.7  717.66   712.3  724.51     742  725.82
   751.9  727.54   761.8  732.14   791.5  750.95   801.4  756.03   811.3  757.97
   831.1  770.76   840.9  776.43   850.8  780.68   890.4  789.27   910.2  792.44
#Mann= 3 , 0 , 0
       0      .1       0   447.4    .045       0   462.4      .1       0
Bank Sta=447.4,462.4
XS Rating Curve= 0 ,0
Exp/Cntr=0.3,0.1

Type RM Length L Ch R = 1 ,23378.4 ,307.5,300.2,293.8
XS GIS Cut Line= 3
     2151299.356      366795.722     2151497.742      366386.903
     2151680.548      365966.608
#Sta/Elev= 30
     9.9   772.6    39.5  770.73    69.1  770.37      79  769.71   158.1  759.45
   167.9   759.3   177.8  758.34   217.3  753.66   237.1  750.47   256.8  746.05
   276.6  743.63   316.1  735.18   345.7  731.58   375.4  730.14   385.3  728.66
   424.8  720.49   444.5  711.65   446.9  711.51   454.4   711.1   461.9  711.46
   493.4  714.14   688.5  719.21   698.2  721.06     747  737.88   766.5  741.38
   795.7   751.3   844.5  766.41     864  769.43   893.2  776.81   912.7  779.51
#Mann= 3 , 0 , 0
       0      .1       0   446.9    .045       0   461.9      .1       0
Bank Sta=446.9,461.9
XS Rating Curve= 0 ,0
Exp/Cntr=0.3,0.1

Type RM Length L Ch R = 1 ,23078.2 ,388.6,387.2,385.8
XS GIS Cut Line= 3
     2151717.431      367018.157     2151774.572      366566.759
     2151831.712      366115.362
#Sta/Elev= 30
     9.9  759.96    29.7  757.94    79.1  756.09   118.7  752.63   128.6  752.48
   158.3  749.58   217.6  746.25   247.3  741.24   257.2  740.37   316.5  740.73
   346.2     739   375.9  736.16   405.5   735.3   415.4  733.87     455  722.21
   484.7  723.28   494.6  722.53     544  714.98   563.8  709.78   568.6  709.29
   573.7  708.78   583.6  709.14   603.4  711.42   781.4  715.12   791.3  717.11
   801.2  721.26   830.9  736.14   840.8  736.32   870.4  750.79     910  763.51
#Mann= 3 , 0 , 0
       0      .1       0   568.6    .045       0   583.6      .1       0
Bank Sta=568.6,583.6
XS Rating Curve= 0 ,0
Exp/Cntr=0.3,0.1

Type RM Length L Ch R = 1 ,22691   ,212.8,212.6,212.3
XS GIS Cut Line= 2
     2152146.736      366920.643      2152204.64      366012.173
#Sta/Elev= 30
     9.9  725.55    89.1  722.25   178.1  719.77   217.7  717.82     376  713.15
   385.9  712.52   395.8  710.24   405.7  709.46   415.6     707   425.5  705.17
   434.9  704.57   445.3  704.48   449.9  705.34   465.1  708.61   474.9   709.3
     564  708.63   613.5   708.6   623.4  709.21   633.3  711.93   653.1  721.03
   672.8  725.64   712.4  744.67   742.1  757.66     752  760.05   761.9  761.52
   791.6  771.03   831.2  784.68   841.1  786.51   850.9  787.35   910.3  802.12
#Mann= 3 , 0 , 0
       0      .1       0   434.9    .045       0   449.9      .1       0
Bank Sta=434.9,449.9
XS Rating Curve= 0 ,0
Exp/Cntr=0.3,0.1

Type RM Length L Ch R = 1 ,22478.4 ,291.8,291.9,292.1
XS GIS Cut Line= 3
     2152361.832       366921.39     2152387.051      366467.082
     2152409.878      366012.656
#Sta/Elev= 30
     9.9  756.87   108.8  748.36   148.4  740.29   158.3  739.96   168.2  738.09
   197.8  730.19   237.4  724.17   247.3  723.81   296.7  717.46   405.6  710.42
   425.3  709.78   447.7  704.91     455  703.96   462.7  704.78   484.7  707.48
   603.4  709.06   613.3  709.79   623.2  711.74   642.9  717.88   672.6  730.61
   692.4  737.77   702.3   743.9   722.1  754.35   751.7  767.32   761.6  770.15
   771.5  771.58     821  790.73   840.8  794.76   860.6  796.65     910  806.12
#Mann= 3 , 0 , 0
       0      .1       0   447.7    .045       0   462.7      .1       0
Bank Sta=447.7,462.7
XS Rating Curve= 0 ,0
Exp/Cntr=0.3,0.1

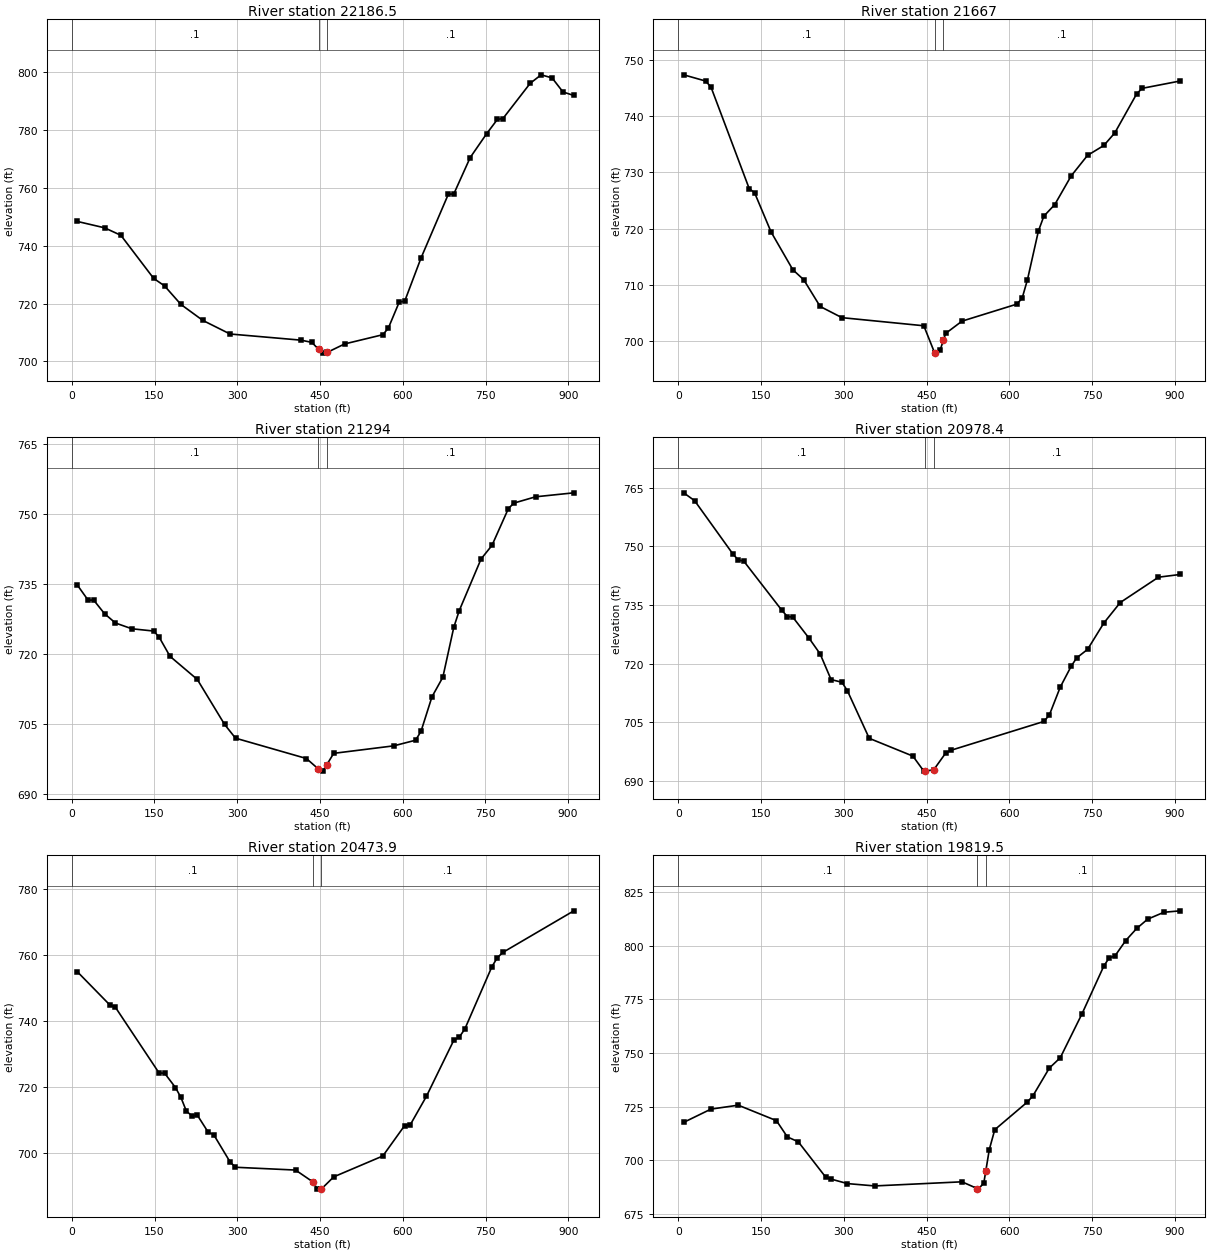
Type RM Length L Ch R = 1 ,22186.5 ,516.3,519.5,522.7
XS GIS Cut Line= 2
     2152650.897      366915.522     2152706.407      366007.072
#Sta/Elev= 30
     9.9  748.44    59.4  746.23      89  743.64   148.4  728.73   168.2  726.12
   197.9   719.7   237.4   714.2   286.9  709.48   415.5  707.35   435.3  706.58
   447.6  704.12   455.1  702.86   462.6  703.08   494.6  706.04   563.9  709.24
   573.8  711.51   593.6  720.54   603.5  720.83   633.1  735.79   682.6  757.86
   692.5  757.95   722.2  770.54   751.9  778.76   771.6  783.77   781.5  784.02
     831  796.24   850.8  799.17   870.6  798.11   890.4  793.24   910.1  792.02
#Mann= 3 , 0 , 0
       0      .1       0   447.6    .045       0   462.6      .1       0
Bank Sta=447.6,462.6
XS Rating Curve= 0 ,0
Exp/Cntr=0.3,0.1

Type RM Length L Ch R = 1 ,21667   ,373.5,373,372.5
XS GIS Cut Line= 2
     2153091.084      367027.971     2153275.325      366136.817
#Sta/Elev= 30
     9.9  747.34    49.5  746.24    59.3  745.18   128.6  727.14   138.5  726.37
   168.2  719.44   207.7  712.72   227.5  710.94   257.2   706.2   296.7  704.21
   445.1  702.77   464.9  697.91   465.7  697.96   474.8  698.47   480.7  700.23
   484.7  701.41   514.3  703.59   613.3   706.6   623.2  707.62     633  710.97
   652.8   719.6   662.7  722.24   682.5   724.3   712.2  729.39   741.8  733.03
   771.5   734.8   791.3  737.03   830.9  743.96   840.8  744.94     910  746.25
#Mann= 3 , 0 , 0
       0      .1       0   465.7    .045       0   480.7      .1       0
Bank Sta=465.7,480.7
XS Rating Curve= 0 ,0
Exp/Cntr=0.3,0.1

Type RM Length L Ch R = 1 ,21294   ,318.6,315.5,312.5
XS GIS Cut Line= 2
     2153469.661      367089.924     2153633.867        366194.2
#Sta/Elev= 30
     9.9  734.82    29.7  731.53    39.6  731.58    59.4  728.64    79.2  726.64
   108.9   725.4   148.5  724.91   158.4  723.62   178.2  719.48   227.7  714.51
   277.2  704.85     297   701.9   425.6  697.53   447.5  695.26   455.3  694.82
   462.5  696.18   475.1  698.64     584  700.25   623.6  701.46   633.5  703.37
   653.3  710.77   673.1     715   692.9   725.7   702.8  729.29   742.4  740.39
   762.2  743.31   791.9   751.2   801.8  752.39   841.4  753.75   910.7   754.6
#Mann= 3 , 0 , 0
       0      .1       0   447.5    .045       0   462.5      .1       0
Bank Sta=447.5,462.5
XS Rating Curve= 0 ,0
Exp/Cntr=0.3,0.1

Type RM Length L Ch R = 1 ,20978.4 ,501.4,504.5,507.8
XS GIS Cut Line= 3
     2153840.004      367147.719     2153861.469      366693.215
     2153884.975      366238.823
#Sta/Elev= 30
     9.9  763.68    29.7  761.67    98.9  748.08   108.8  746.51   118.7  746.24
   187.9  733.64   197.8  732.06   207.7   731.9   237.4  726.47   257.2  722.51
     277  715.96   296.7  715.27   306.6   713.1   346.2  700.94   425.3   696.4
   445.1  692.56   447.8  692.62   462.8  692.85   484.7  697.17   494.6   697.9
   662.7  705.25   672.6  706.89   692.4  714.03   712.2  719.36   722.1  721.49
   741.9  723.67   771.5  730.43   801.2  735.65   870.4  742.12     910  742.82
#Mann= 3 , 0 , 0
       0      .1       0   447.8    .045       0   462.8      .1       0
Bank Sta=447.8,462.8
XS Rating Curve= 0 ,0
Exp/Cntr=0.3,0.1

Type RM Length L Ch R = 1 ,20473.9 ,647.3,654.4,661.4
XS GIS Cut Line= 3
     2154281.231      367166.242     2154363.876        366718.8
     2154448.527      366271.745
#Sta/Elev= 30
     9.9  754.85    69.2  744.71    79.1  744.04   158.3  724.11   168.2  724.07
   187.9  719.72   197.8  716.72   207.7  712.57   217.6  711.14   227.5  711.35
   247.3  706.15   257.2  705.44   286.9  697.16   296.7  695.54   405.6  694.69
   437.2  691.08   445.1  688.93   452.2  688.91   474.8  692.63   563.8  698.96
   603.4   708.2   613.3  708.35   642.9  717.08   692.4  734.05   702.3  735.01
   712.2  737.38   761.6  756.39   771.5  759.12   781.4  760.69     910  773.29
#Mann= 3 , 0 , 0
       0      .1       0   437.2    .045       0   452.2      .1       0
Bank Sta=437.2,452.2
XS Rating Curve= 0 ,0
Exp/Cntr=0.3,0.1

Type RM Length L Ch R = 1 ,19819.5 ,309.8,312.4,315
XS GIS Cut Line= 3
     2154721.894      367307.055     2154939.634      366907.538
     2155157.373       366508.02
#Sta/Elev= 30
     9.9   717.7    59.3  723.88   108.8  725.71     178   718.5   197.8  710.91
   217.6  708.64   267.1  692.21     277  691.26   306.6  689.16   356.1  688.07
   514.3  689.99   542.4   686.8     544  686.58   553.9  689.49   557.4  694.99
   563.8  705.03   573.7  714.28     633  727.23   642.9   730.1   672.6  743.01
   692.4  747.81     732   768.4   771.5  790.64   781.4  794.47   791.3  795.18
   811.1  802.46   830.9  808.07   850.7   812.4   880.3  815.63     910   816.3
#Mann= 3 , 0 , 0
       0      .1       0   542.4    .045       0   557.4      .1       0
Bank Sta=542.4,557.4
XS Rating Curve= 0 ,0
Exp/Cntr=0.3,0.1

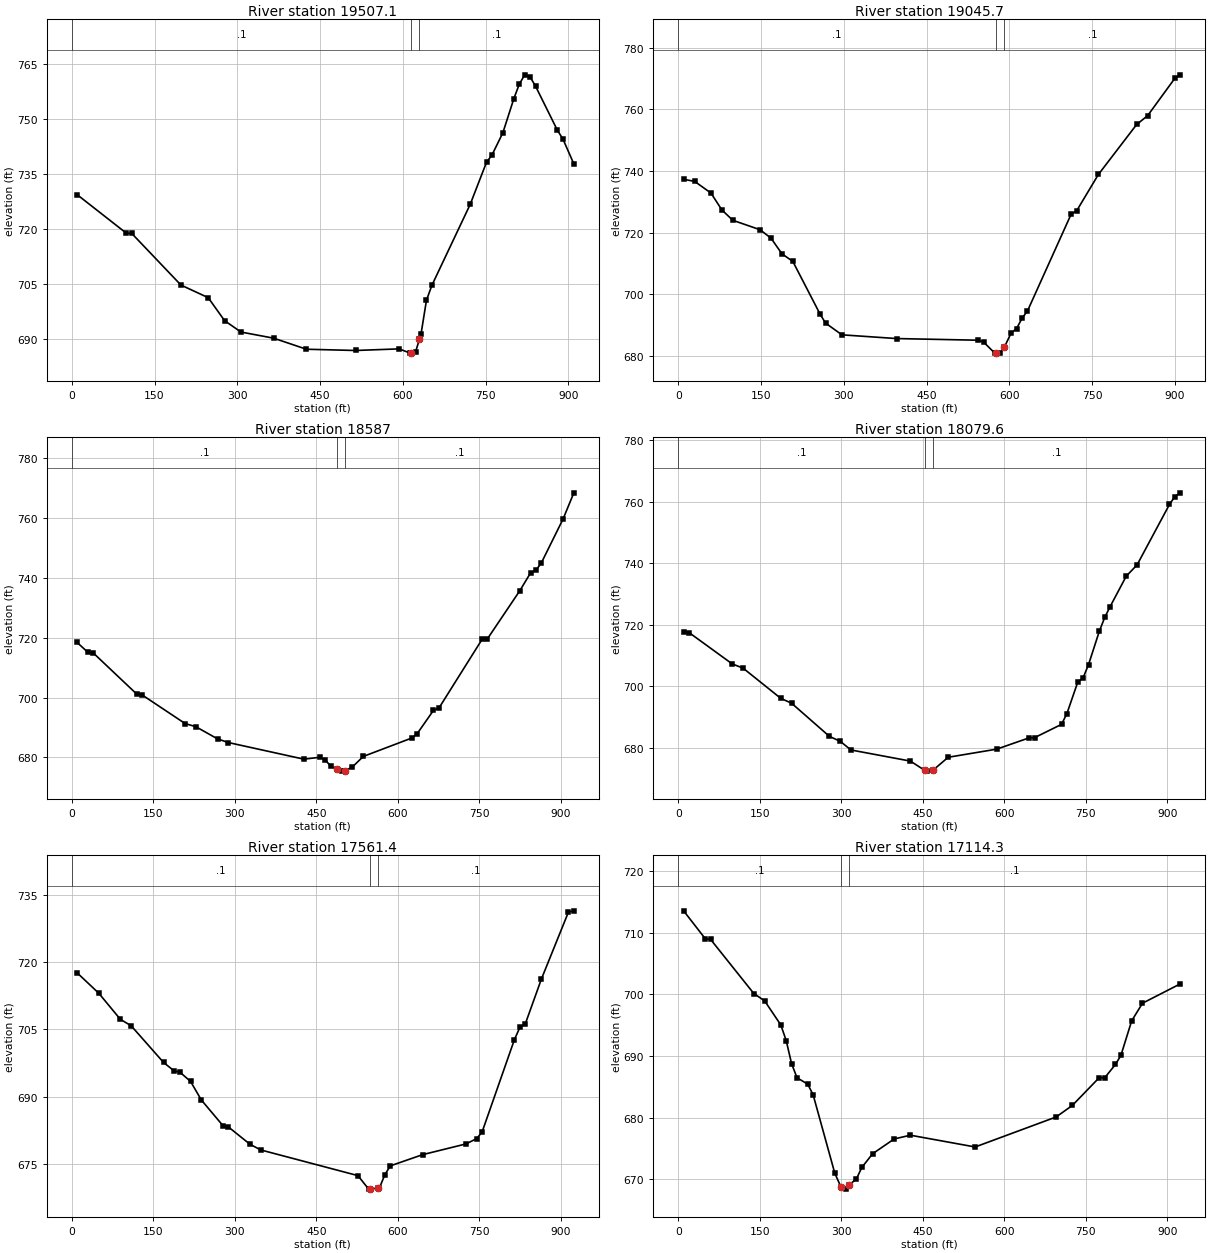
Type RM Length L Ch R = 1 ,19507.1 ,461.2,461.3,461.5
XS GIS Cut Line= 3
     2154895.993       367487.98     2155158.887      367116.616
     2155421.781      366745.251
#Sta/Elev= 30
     9.9  729.44    98.9  718.96   108.8  718.88   197.8  704.83   247.3  701.38
     277  695.12   306.6  692.02     366  690.34   425.3  687.33   514.3  686.99
   593.5  687.43   613.3  686.27     615  686.34   623.2  686.64     630  689.99
     633  691.46   642.9   700.7   652.8  704.78   722.1   726.8   751.7  738.29
   761.6  740.26   781.4  746.35   801.2   755.6   811.1  759.58     821  762.12
   830.9  761.49   840.8  758.96   880.3  746.97   890.2  744.63     910  737.83
#Mann= 3 , 0 , 0
       0      .1       0     615    .045       0     630      .1       0
Bank Sta=615,630
XS Rating Curve= 0 ,0
Exp/Cntr=0.3,0.1

Type RM Length L Ch R = 1 ,19045.7 ,469.6,458.8,448
XS GIS Cut Line= 3
     2155311.873       367687.93     2155577.288      367318.363
     2155842.702      366948.795
#Sta/Elev= 30
     9.9  737.29    29.7  736.63    59.3  732.83    79.1  727.35    98.9  723.99
   148.4  720.92   168.2  718.17   187.9  713.12   207.7  710.63   257.2  693.48
   267.1   690.6   296.7   686.8   395.7  685.59     544  685.05   553.9  684.38
   573.7  680.86   576.2  680.87   583.6  680.89   591.2  682.84   603.4   687.4
   613.3  688.85   623.2   692.2     633  694.55   712.2     726   722.1  727.07
   761.6  738.88   830.9   755.1   850.7  757.95   900.1  770.09     910  771.22
#Mann= 3 , 0 , 0
       0      .1       0   576.2    .045       0   591.2      .1       0
Bank Sta=576.2,591.2
XS Rating Curve= 0 ,0
Exp/Cntr=0.3,0.1

Type RM Length L Ch R = 1 ,18587   ,505.2,507.4,509.6
XS GIS Cut Line= 2
     2155883.948       367994.66     2156095.614      367095.272
#Sta/Elev= 30
     9.9  718.45    29.8  715.14    39.7  714.92   119.2  701.25   129.2  700.94
   208.6  691.34   228.5  690.27   268.2  686.22   288.1  684.99   427.2  679.43
     457  680.07   466.9  679.09   476.9     677   487.7  676.17   496.8  675.43
   502.7  675.52   516.6  676.85   536.5  680.34   625.9  686.51   635.8  687.99
   665.6  695.73   675.6  696.48   755.1  719.49     765  719.68   824.6  735.77
   844.5  741.76   854.4  742.62   864.3   745.1   904.1  759.71     924  768.49
#Mann= 3 , 0 , 0
       0      .1       0   487.7    .045       0   502.7      .1       0
Bank Sta=487.7,502.7
XS Rating Curve= 0 ,0
Exp/Cntr=0.3,0.1

Type RM Length L Ch R = 1 ,18079.6 ,518.5,518.2,517.9
XS GIS Cut Line= 2
     2156315.114      368214.243     2156537.115       367317.35
#Sta/Elev= 30
     9.9  717.72    19.9   717.5    99.4  707.32   119.2  705.97   188.8  696.13
   208.6  694.56   278.2   683.8   298.1  682.19   317.9  679.38   427.2  675.77
   453.8  672.75     457  672.51   468.8   672.8   496.8  677.01   586.2  679.65
   645.8  683.32   655.7  683.37   705.4   687.7   715.3   691.2   735.2  701.39
   745.1   702.8   755.1   707.1   774.9   717.9   784.9  722.42   794.8  725.93
   824.6  735.84   844.5   739.5   904.1  759.13     914  761.68     924  762.88
#Mann= 3 , 0 , 0
       0      .1       0   453.8    .045       0   468.8      .1       0
Bank Sta=453.8,468.8
XS Rating Curve= 0 ,0
Exp/Cntr=0.3,0.1

Type RM Length L Ch R = 1 ,17561.4 ,447.3,447.2,447
XS GIS Cut Line= 2
     2156784.847      368446.483     2157006.848      367549.589
#Sta/Elev= 30
     9.9  717.56    49.7  713.02    89.4  707.21   109.3  705.77   168.9   697.6
   188.8  695.68   198.7  695.47   218.6  693.38   238.4  689.25   278.2  683.53
   288.1  683.25   327.9  679.39   347.7  678.12   526.6   672.4   546.4  669.39
   548.2   669.4   563.2  669.62   566.3  669.69   576.2  672.59   586.2  674.57
   645.8  677.07   725.3  679.45   745.1  680.63   755.1   682.1   814.7  702.71
   824.6  705.39   834.5  706.14   864.3  716.18     914  731.08     924  731.37
#Mann= 3 , 0 , 0
       0      .1       0   548.2    .045       0   563.2      .1       0
Bank Sta=548.2,563.2
XS Rating Curve= 0 ,0
Exp/Cntr=0.3,0.1

Type RM Length L Ch R = 1 ,17114.3 ,694.8,692.9,691
XS GIS Cut Line= 2
     2157123.131      368553.138     2157325.993      367651.723
#Sta/Elev= 30
     9.9  713.57    49.7  709.05    59.6  708.93   139.1  700.15     159  698.96
   188.8  695.05   198.7  692.51   208.6  688.77   218.6  686.48   238.4  685.44
   248.4  683.67   288.1     671   299.6  668.72     308  668.41   314.6   669.1
   327.9  670.06   337.8  671.92   357.7  674.15   397.4  676.55   427.2  677.16
   546.4  675.25   695.5  680.12   725.3  681.99   774.9  686.51   784.9  686.48
   804.7  688.65   814.7  690.12   834.5  695.72   854.4  698.58     924  701.72
#Mann= 3 , 0 , 0
       0      .1       0   299.6    .045       0   314.6      .1       0
Bank Sta=299.6,314.6
XS Rating Curve= 0 ,0
Exp/Cntr=0.3,0.1

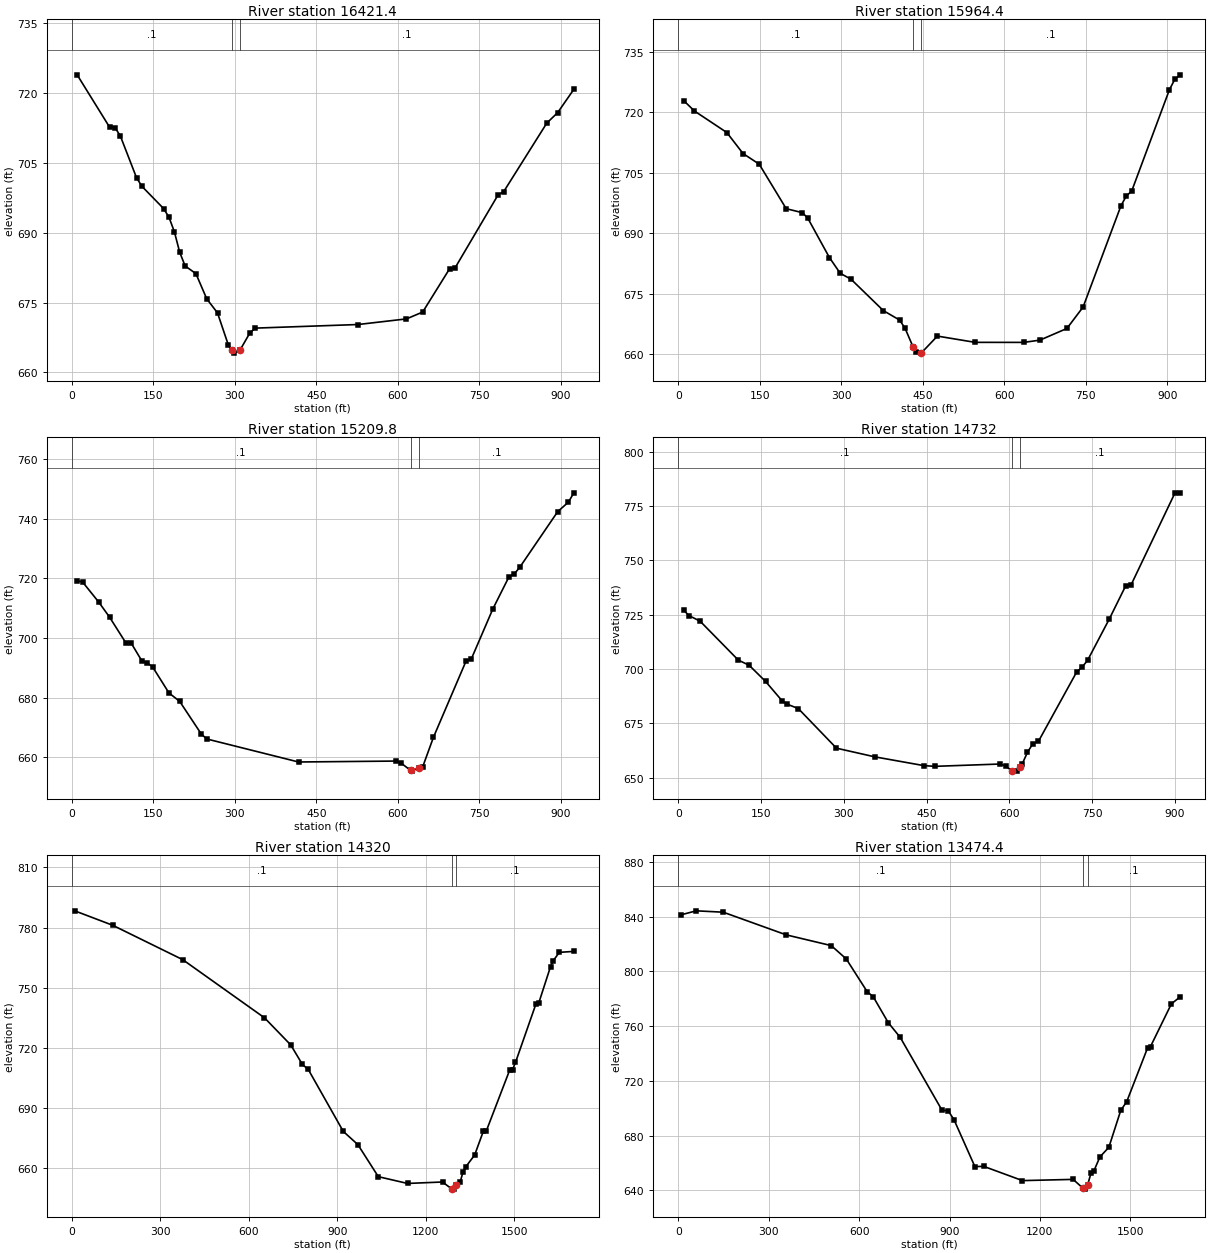
Type RM Length L Ch R = 1 ,16421.4 ,458.8,456.9,455.6
XS GIS Cut Line= 2
     2157790.624      368713.322      2157940.47      367801.594
#Sta/Elev= 30
     9.9   723.9    69.5  712.68    79.5  712.58    89.4  710.77   119.2   701.8
   129.2  699.95   168.9   695.2   178.8  693.35   188.8  690.21   198.7  685.78
   208.6  682.87   228.5  681.21   248.4   675.8   268.2  672.79   288.1  665.91
   294.8  664.73   298.1  664.15   309.8  664.83   327.9  668.51   337.8  669.52
   526.6  670.29     616   671.5   645.8  672.97   695.5  682.29   705.4  682.45
   784.9  698.19   794.8   698.8   874.3  713.55   894.2  715.78     924  720.79
#Mann= 3 , 0 , 0
       0      .1       0   294.8    .045       0   309.8      .1       0
Bank Sta=294.8,309.8
XS Rating Curve= 0 ,0
Exp/Cntr=0.3,0.1

Type RM Length L Ch R = 1 ,15964.4 ,750.9,754.6,757.8
XS GIS Cut Line= 2
      2158274.05      368827.732     2158288.739      367903.889
#Sta/Elev= 30
     9.9  722.88    29.8  720.29    89.4  714.96   119.2  709.76     149  707.12
   198.7  696.09   228.5   695.1   238.4  693.75   278.2  683.99   298.1  680.09
   317.9  678.63   377.5  670.84   407.3  668.51   417.3  666.51   432.5  661.75
   437.1  660.51   447.1  660.31   447.5  660.37   476.9  664.53   546.4  662.98
   635.8  662.97   665.6  663.53   715.3  666.42   745.1  671.73   814.7  696.79
   824.6  699.24   834.5  700.44   904.1  725.61     914  728.16     924  729.25
#Mann= 3 , 0 , 0
       0      .1       0   432.5    .045       0   447.5      .1       0
Bank Sta=432.5,447.5
XS Rating Curve= 0 ,0
Exp/Cntr=0.3,0.1

Type RM Length L Ch R = 1 ,15209.8 ,481.5,477.7,473.9
XS GIS Cut Line= 2
     2158824.259       368850.64     2158988.923      367941.471
#Sta/Elev= 30
     9.9  719.19    19.9  718.77    49.7  712.02    69.5  707.01    99.4  698.42
   109.3  698.32   129.2  692.27   139.1  691.66     149  690.27   178.8  681.63
   198.7  678.76   238.4  667.85   248.4   666.2   417.3  658.49   596.1   658.8
     606  658.15   623.6  655.66   625.9  655.43   638.6  656.62   645.8  656.84
   665.6  666.76   725.3  692.16   735.2  692.95   774.9  709.73   804.7  720.53
   814.7  721.54   824.6  723.73   894.2  742.31     914  745.52     924  748.63
#Mann= 3 , 0 , 0
       0      .1       0   623.6    .045       0   638.6      .1       0
Bank Sta=623.6,638.6
XS Rating Curve= 0 ,0
Exp/Cntr=0.3,0.1

Type RM Length L Ch R = 1 ,14732   ,413.3,412,411.9
XS GIS Cut Line= 3
     2159398.412      368926.087     2159403.424      368471.114
     2159408.435      368016.142
#Sta/Elev= 30
     9.9  726.97    19.8  724.53    39.6     722   108.8   704.1   128.6  701.69
   158.3  694.26   187.9  685.45   197.8  683.76   217.6  681.78   286.8  663.55
   356.1  659.57   445.1  655.53   464.9  655.19   583.6  656.26   593.5  655.31
   604.1  653.24   613.3  652.99   619.1  654.84   623.2  656.15     633  661.67
   642.9  665.68   652.8  666.67   722.1  698.59     732  700.87   741.8  703.92
   781.4  723.05   811.1  738.32     821  738.82   900.1   780.9     910  781.06
#Mann= 3 , 0 , 0
       0      .1       0   604.1    .045       0   619.1      .1       0
Bank Sta=604.1,619.1
XS Rating Curve= 0 ,0
Exp/Cntr=0.3,0.1

Type RM Length L Ch R = 1 ,14320   ,854.9,845.6,835.1
XS GIS Cut Line= 3
     2159216.984      369295.904     2159783.819      369036.568
     2159823.652      367959.199
#Sta/Elev= 30
     9.9  788.35   138.5  781.15     376  763.97     653  734.94     742   721.4
   781.6  711.64   801.4  709.14   920.1   678.2   969.5  671.62  1038.8  655.61
  1137.7  652.23  1256.4  652.95  1287.5  649.49  1295.9  649.39  1302.5  651.43
  1315.7  652.71  1325.6  657.81  1335.5   660.6  1365.2   666.4  1394.8  678.34
  1404.7  678.41  1483.8  708.77  1493.7  709.09  1503.6  712.63  1572.9  741.84
  1582.8  742.46  1622.3  760.46  1632.2  763.54    1652  767.62  1701.4  768.09
#Mann= 3 , 0 , 0
       0      .1       0  1287.5    .045       0  1302.5      .1       0
Bank Sta=1287.5,1302.5
XS Rating Curve= 0 ,0
Exp/Cntr=0.3,0.1

Type RM Length L Ch R = 1 ,13474.4 ,291.4,287,282.7
XS GIS Cut Line= 3
     2160917.489      369525.602     2160752.492      368726.309
     2160387.432      367959.153
#Sta/Elev= 30
      10  841.39    59.7  844.27   149.3  843.27   358.3  826.71   507.6  818.87
   557.4  809.14     627  785.16   646.9  781.52   696.7  762.61   736.5  751.81
   875.4  698.49   895.2  698.35   914.9  691.69   984.1  657.46  1013.7  657.59
  1142.1   647.2  1310.1   648.1  1343.3  641.53  1349.6  640.98  1358.3  644.09
  1369.4  652.73  1379.2   654.4    1399  664.52  1428.6  671.51  1468.2  698.54
  1487.9  704.86  1557.1  744.15  1566.9  745.16  1636.1  776.31  1665.7  781.54
#Mann= 3 , 0 , 0
       0      .1       0  1343.3    .045       0  1358.3      .1       0
Bank Sta=1343.3,1358.3
XS Rating Curve= 0 ,0
Exp/Cntr=0.3,0.1