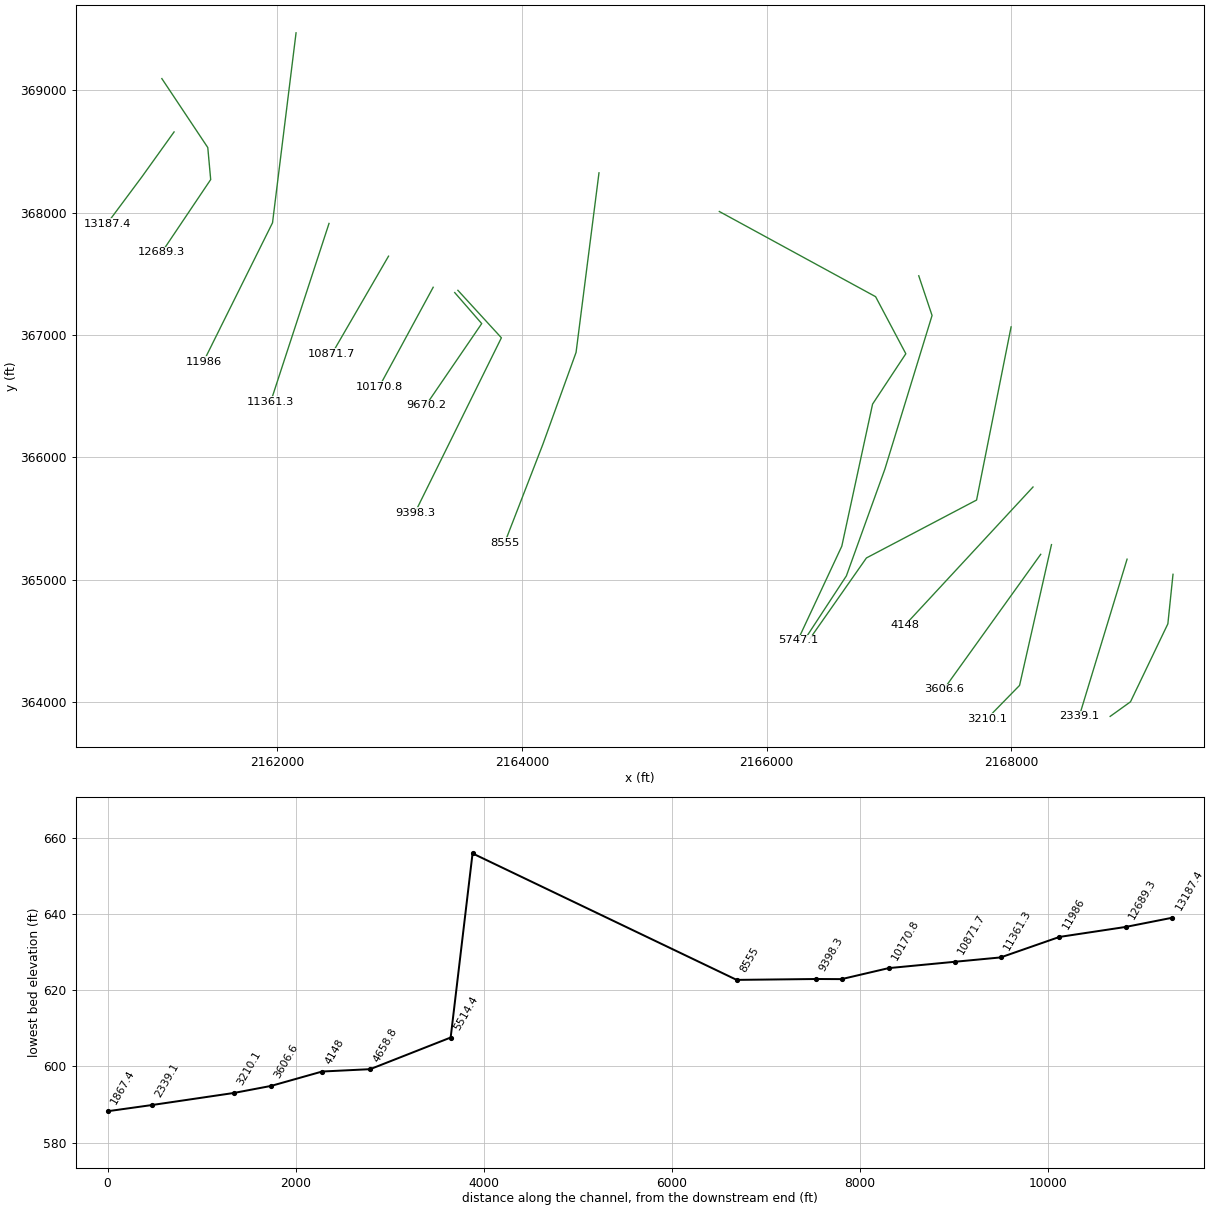
HEC-RAS study HRSSHRN.prj: HRSSHRN

--- HRSSHRN.g01 (geometry) --- (continued)

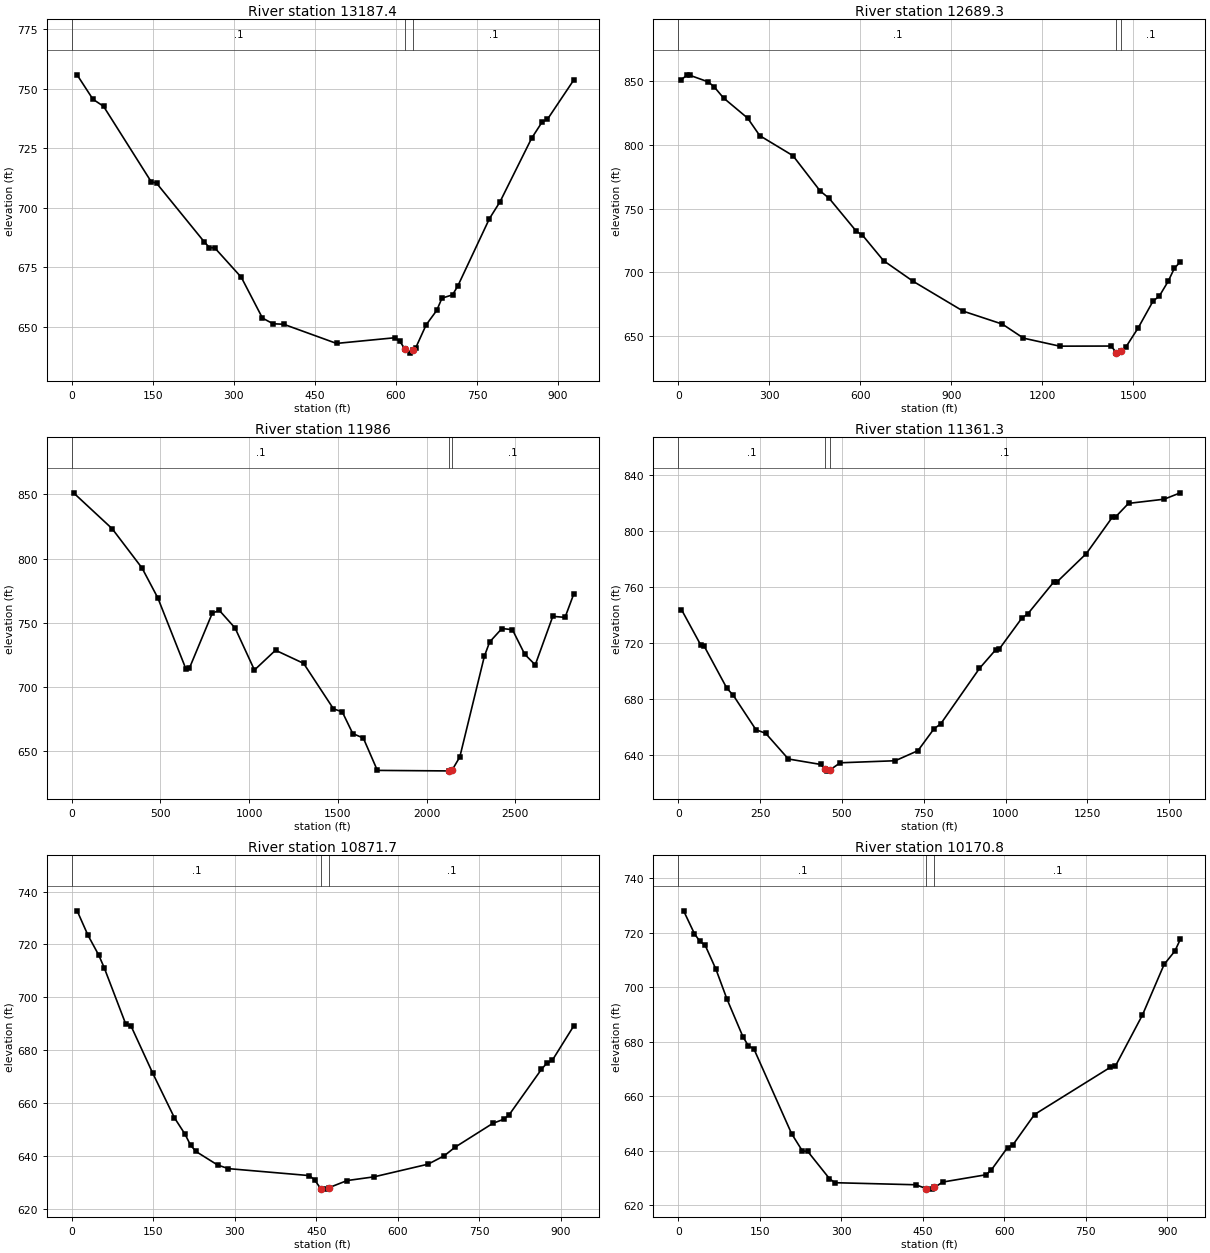
Type RM Length L Ch R = 1 ,13187.4 ,496.9,498.1,499.4
XS GIS Cut Line= 3
     2161158.085      368660.239     2160895.455       368293.74
     2160609.919      367910.129
#Sta/Elev= 30
     9.8  755.77    39.2  745.52    58.8  742.57     147  710.93   156.8  710.36
     245  685.76   254.8  683.33   264.6   683.2   313.7  670.88   352.9  653.76
   372.5  651.38   392.1  651.18   489.9  643.14   597.3  645.51     607  644.03
   617.1   640.6   626.6  639.07   632.1  640.27   636.3  641.19   655.8  650.93
   675.4     657   685.1  662.13   704.6  663.51   714.4  667.24   772.9  695.47
   792.5  702.54     851  729.19   870.5  736.02   880.3  737.14   929.1  753.65
#Mann= 3 , 0 , 0
       0      .1       0   617.1    .045       0   632.1      .1       0
Bank Sta=617.1,632.1
XS Rating Curve= 0 ,0
Exp/Cntr=0.3,0.1

Type RM Length L Ch R = 1 ,12689.3 ,700.3,703.2,706.2
XS GIS Cut Line= 4
     2161058.272      369095.845     2161433.485      368532.471
     2161457.246      368270.871     2161057.777      367676.763
#Sta/Elev= 30
      10     851    29.9  854.84    39.8  854.35    99.5  849.26   119.5  845.13
   149.3  836.71   228.9  820.88   268.8  807.15   378.3  791.43   467.8  763.82
   497.7  757.98   587.3  732.16   607.2   729.2   676.9  709.15   774.2     693
   939.6  669.54  1068.8  659.38  1138.4  648.38  1257.7  642.11  1426.8  642.19
  1444.7  637.12  1446.7  636.64  1459.7  638.21  1476.5   641.6  1516.3   656.3
    1566  677.59  1585.9  681.19  1615.7  693.05  1635.6  703.02  1655.5  708.31
#Mann= 3 , 0 , 0
       0      .1       0  1444.7    .045       0  1459.7      .1       0
Bank Sta=1444.7,1459.7
XS Rating Curve= 0 ,0
Exp/Cntr=0.3,0.1

Type RM Length L Ch R = 1 ,11986   ,621.4,624.7,628
XS GIS Cut Line= 3
     2162154.894       369470.03     2161962.532      367917.581
     2161399.114      366784.047
#Sta/Elev= 30
     9.9  851.28   227.7  823.27     396   792.6   485.1  769.25   643.6  713.75
   663.4  714.49   792.1  757.34   831.7  759.51   920.8   745.7  1029.7  712.94
  1148.5   728.4  1306.9  718.14  1475.2  682.64  1524.7  680.29  1584.1  663.31
  1643.4  659.85  1722.6  634.59  2128.9  634.17  2137.9  634.02  2143.9  634.85
  2187.4  645.07  2325.8  723.68  2355.5  734.83  2424.7  745.36    2484  744.44
  2553.3  725.27  2612.6  716.95  2711.5  754.84  2780.7  754.06  2830.2   772.5
#Mann= 3 , 0 , 0
       0      .1       0  2128.9    .045       0  2143.9      .1       0
Bank Sta=2128.9,2143.9
XS Rating Curve= 0 ,0
Exp/Cntr=0.3,0.1

Type RM Length L Ch R = 1 ,11361.3 ,493.6,489.6,487.7
XS GIS Cut Line= 2
     2162424.237      367912.347     2161947.425      366454.319
#Sta/Elev= 30
     9.9  743.85    69.3  718.36    79.2   717.8   148.5  687.79   168.2  682.71
   237.5  658.15   267.2  655.62   336.5  637.29   435.5   633.4   447.2  630.17
   455.3  628.64   462.2  629.25   494.8  634.59   663.1  636.05   732.4  643.23
   781.9  658.97   801.6  662.22   920.4  701.92   969.9  715.18   979.8   715.4
  1049.1  737.53  1068.9  741.06    1148  763.73  1157.9  763.76    1247  783.83
  1326.2   809.7  1336.1  809.93  1375.7   819.6  1484.5  822.58    1534  827.13
#Mann= 3 , 0 , 0
       0      .1       0   447.2    .045       0   462.2      .1       0
Bank Sta=447.2,462.2
XS Rating Curve= 0 ,0
Exp/Cntr=0.3,0.1

Type RM Length L Ch R = 1 ,10871.7 ,697.3,700.9,687.7
XS GIS Cut Line= 2
     2162910.617      367644.861     2162447.171      366845.536
#Sta/Elev= 30
     9.9   732.7    29.8  723.47    49.7  715.93    59.6  711.24    99.4  689.86
   109.3  689.05     149  671.32   188.8  654.51   208.6   648.2   218.6  644.11
   228.5  641.73   268.2  636.63   288.1  635.24   437.1  632.61   447.1  630.94
   458.3  627.62   466.9  627.49   473.3  628.04   506.7  630.73   556.4  632.14
   655.7  636.92   685.5   640.1   705.4  643.34   774.9  652.36   794.8  653.89
   804.7  655.52   864.3  672.76   874.3  675.11   884.2  676.14     924  689.25
#Mann= 3 , 0 , 0
       0      .1       0   458.3    .045       0   473.3      .1       0
Bank Sta=458.3,473.3
XS Rating Curve= 0 ,0
Exp/Cntr=0.3,0.1

Type RM Length L Ch R = 1 ,10170.8 ,499.5,500.6,502.2
XS GIS Cut Line= 2
     2163275.561      367390.705      2162834.99      366578.548
#Sta/Elev= 30
     9.9  728.01    29.8  719.62    39.7  716.83    49.7   715.3    69.5   706.5
    89.4  695.75   119.2  681.72   129.2  678.41   139.1  677.38   208.6   646.2
   228.5  639.84   238.4  639.66   278.2  629.71   288.1  628.19   437.1  627.43
   456.6  626.03   466.9  625.83   471.6  626.47   486.8  628.43   566.3   631.1
   576.2  632.86     606   641.1     616  642.11   655.7  653.23   794.8  670.51
   804.7  671.06   854.4   689.8   894.2  708.33     914  713.24     924  717.54
#Mann= 3 , 0 , 0
       0      .1       0   456.6    .045       0   471.6      .1       0
Bank Sta=456.6,471.6
XS Rating Curve= 0 ,0
Exp/Cntr=0.3,0.1

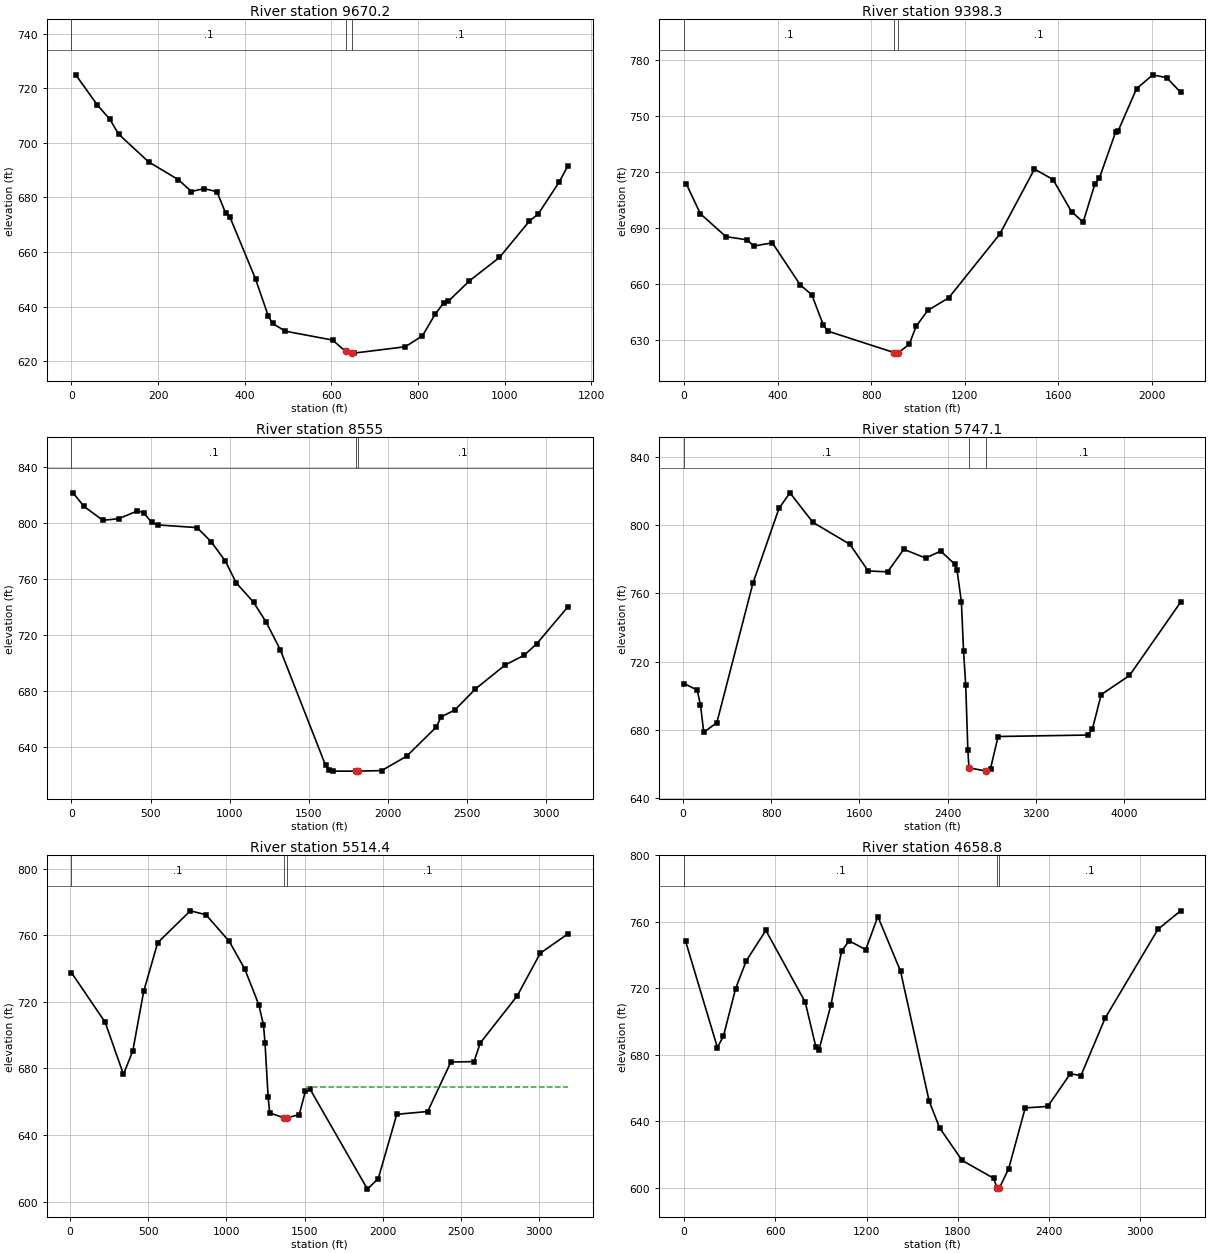
Type RM Length L Ch R = 1 ,9670.2  ,269.1,271.9,276.3
XS GIS Cut Line= 3
     2163451.576      367347.177     2163672.108      367093.918
     2163215.066      366425.136
#Sta/Elev= 30
     9.9  724.91    59.3  713.93    88.9  708.55   108.6  703.21   177.8  693.04
   246.9  686.47   276.6  682.16   306.2  683.21   335.8  682.08   355.6   674.3
   365.5  672.86   424.7  650.13   454.4  636.47   464.2   633.8   493.9  630.97
   602.5  627.73   632.6   623.6   647.6     623   651.9  622.94   770.5  625.28
     810  629.27   839.6  637.28   859.4  641.37   869.3  641.87   918.6  649.45
   987.8     658  1056.9  671.33  1076.7  673.81  1126.1  685.74  1145.9  691.63
#Mann= 3 , 0 , 0
       0      .1       0   632.6    .045       0   647.6      .1       0
Bank Sta=632.6,647.6
XS Rating Curve= 0 ,0
Exp/Cntr=0.3,0.1

Type RM Length L Ch R = 1 ,9398.3  ,838,843.3,839.8
XS GIS Cut Line= 3
     2163477.509      367365.701     2163832.951      366977.831
     2163125.553      365546.642
#Sta/Elev= 30
     9.9  713.61    69.5  697.76   178.7  685.49     268  683.78   297.8  680.44
   377.2  682.14   496.3  659.63   545.9  654.26   595.5  637.95   615.3  634.74
   898.1  623.25   912.8  622.97   913.1  622.98   962.4  627.67   992.2  637.42
  1041.7  645.88    1131   652.6  1349.1  686.75  1497.9  721.72  1577.2  716.13
  1656.5  698.83  1706.1  693.28  1755.7  713.55  1775.5  716.92  1844.9  741.63
  1854.8  741.97  1934.2  764.81  2003.6   772.3  2063.1  770.77  2122.6  762.95
#Mann= 3 , 0 , 0
       0      .1       0   898.1    .045       0   913.1      .1       0
Bank Sta=898.1,913.1
XS Rating Curve= 0 ,0
Exp/Cntr=0.3,0.1

Type RM Length L Ch R = 1 ,8555    ,2804,2807.8,2811.4
XS GIS Cut Line= 4
     2164630.527         368326.     2164443.163      366858.253
     2164171.658      366106.661     2163859.742      365301.902
#Sta/Elev= 30
     9.9  821.26    79.4  811.51   198.6  801.68   297.9  802.79   417.1  808.32
   456.8  807.12   506.5  800.17   546.2  798.36   794.4  796.46   883.8  786.39
   973.2  772.66  1042.7  757.02  1151.9  743.23  1231.4  729.11  1320.8  709.47
  1607.9  626.82  1627.6  623.53  1657.2  622.74  1800.8  622.74  1815.8  622.74
  1963.1  623.12  2120.9  633.39  2308.5  654.18  2338.3  661.33  2427.6  666.48
  2556.6  681.41  2745.1   698.5  2864.1  705.34  2943.5   713.5  3141.9  740.02
#Mann= 3 , 0 , 0
       0      .1       0  1800.8    .045       0  1815.8      .1       0
Bank Sta=1800.8,1815.8
XS Rating Curve= 0 ,0
Exp/Cntr=0.3,0.1

Type RM Length L Ch R = 1 ,5747.1  ,234.7,232.7,231
XS GIS Cut Line= 6
     2165614.084      368009.857     2166890.993      367313.871
     2167138.115      366847.399     2166866.393      366436.106
     2166614.879      365274.844     2166255.525      364506.605
#Sta/Elev= 30
     9.9  707.19   128.6  703.39   158.3  694.65     188  678.65   306.7  684.34
   633.2  765.77   870.6  809.73   969.5   818.8  1177.3  801.53  1512.9   788.7
  1679.1  773.07  1855.1  772.57  2001.9  785.75  2199.1  780.66  2337.1  784.67
  2465.2  777.01  2484.9  773.39    2524  755.13  2543.6  726.16  2563.1  706.55
  2582.7  668.51  2592.5  657.92    2749  655.96  2788.1  657.44  2856.9  676.22
  3673.4  677.08  3712.8  680.85  3791.7  700.71  4048.1  711.92  4511.6  754.79
#Mann= 3 , 0 , 0
     9.9      .1       0  2592.5    .045       0    2749      .1       0
Bank Sta=2592.5,2749
XS Rating Curve= 0 ,0
Exp/Cntr=0.3,0.1

Type RM Length L Ch R = 1 ,5514.4  ,874.5,855.6,836.8
XS GIS Cut Line= 5
     2167243.698      367484.476     2167352.438      367160.182
     2166967.098      365905.396      2166652.29      365032.059
     2166323.189      364529.758
#Sta/Elev= 30
     9.8   737.5   224.8  707.79     342  676.49   401.7  690.58   471.3  726.29
   560.8   755.5   769.6  774.63   869.1   772.3  1018.2  756.31  1117.7  739.65
  1207.2  718.25    1237  706.18    1247  695.23  1266.8  662.82  1276.8  653.38
    1371  650.27    1386  650.32  1465.7  652.33  1505.5  666.59  1535.3  667.51
  1901.6   607.6  1970.7   613.9  2089.2   652.5  2286.7  654.19  2434.9  683.89
    2583  684.14  2622.4  695.27  2858.6  723.52  3006.3  749.17  3183.5  760.81
#Mann= 3 , 0 , 0
     9.8      .1       0    1371    .045       0    1386      .1       0
#XS Ineff= 2 , 0
                         1515.94          668.98
Permanent Ineff=
       F       F
Bank Sta=1371,1386
XS Rating Curve= 0 ,0
Exp/Cntr=0.3,0.1

Type RM Length L Ch R = 1 ,4658.8  ,503.1,510.9,518.7
XS GIS Cut Line= 4
     2167998.314      367066.997     2167716.144      365651.869
     2166816.062      365178.606      2166354.73       364519.83
#Sta/Elev= 30
      10  748.21   218.9  684.39   258.7  691.29   338.4  719.73     408   736.4
   537.4  754.82   796.1  711.71   865.8  684.91   885.7  682.62   965.3  709.99
    1035  742.25  1084.7  748.52  1194.2  743.24  1273.8  763.14  1423.1  730.22
  1610.8   652.3  1679.9  636.08    1828  616.52  2035.4  605.81  2057.1  599.95
    2065  599.29  2072.1  599.83  2134.1  611.63  2242.7  648.09  2390.8     649
  2539.3  668.67  2608.8  667.46  2767.7  701.98  3115.2  755.41  3264.2  766.55
#Mann= 3 , 0 , 0
       0      .1       0  2057.1    .045       0  2072.1      .1       0
Bank Sta=2057.1,2072.1
XS Rating Curve= 0 ,0
Exp/Cntr=0.3,0.1

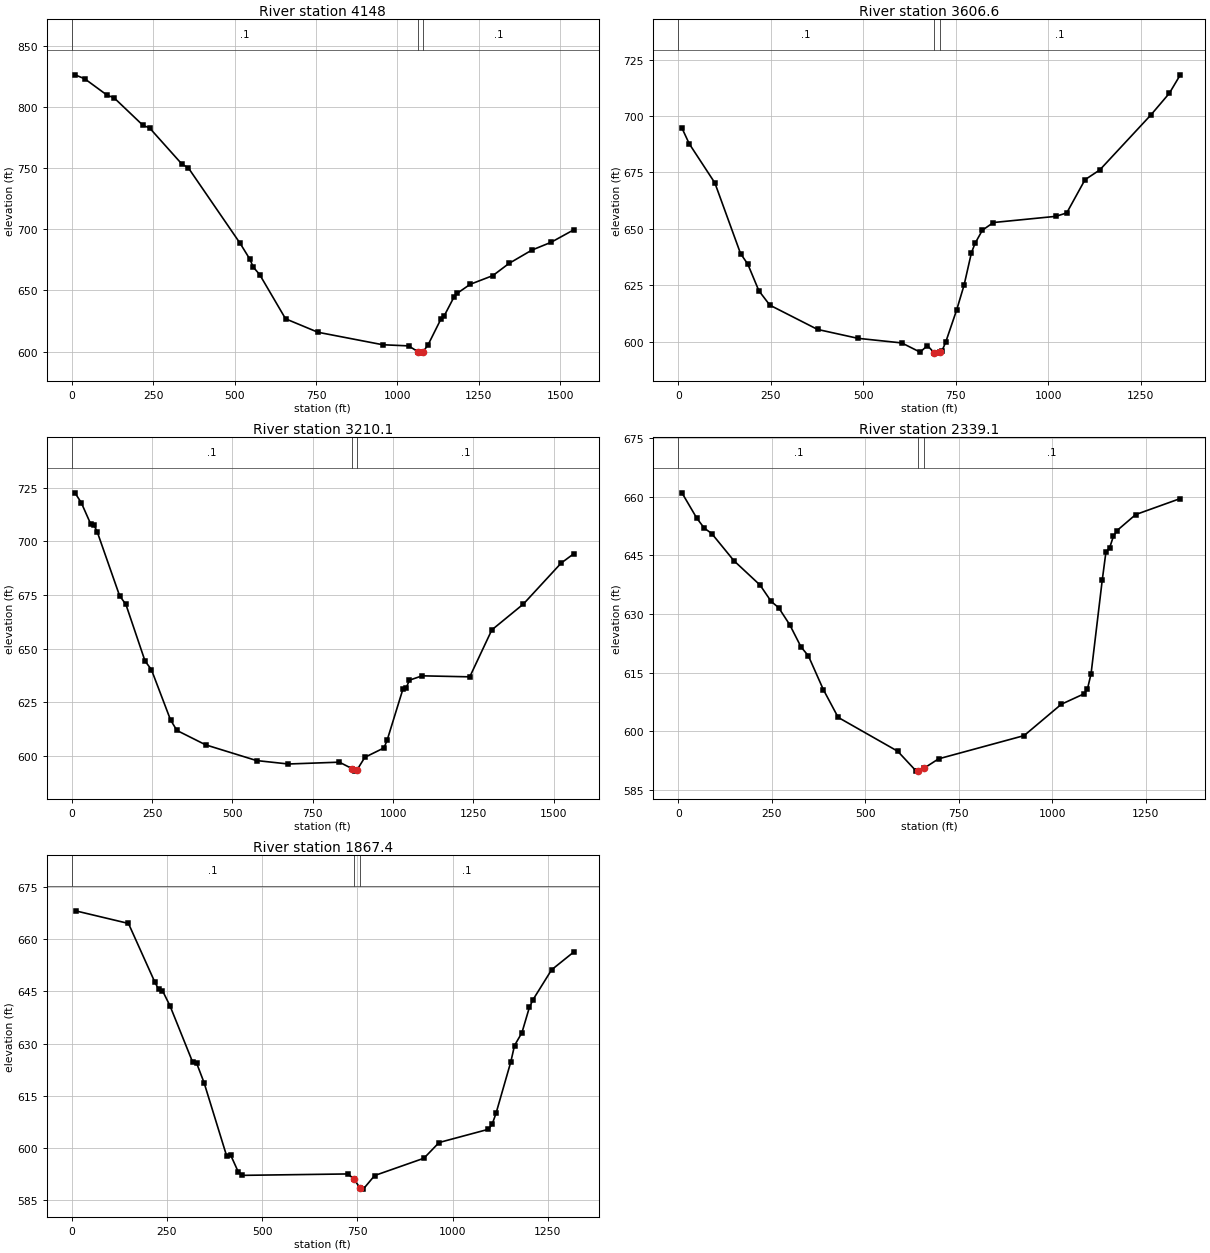
Type RM Length L Ch R = 1 ,4148    ,538.9,541.3,543.8
XS GIS Cut Line= 2
     2168177.473      365758.361     2167129.682      364627.752
#Sta/Elev= 30
     9.9  826.06    39.8  822.82   109.4  809.25   129.3  807.42   218.8  784.73
   238.7  782.71   338.1  753.13     358     750   517.1  688.29     547  675.32
   556.9  669.05   576.8  662.89   656.4  626.71   755.8  615.72   954.7  605.52
  1034.3  604.58  1063.2  599.76  1074.1  598.67  1078.2  599.62  1093.9  605.43
  1133.7  626.67  1143.7  629.25  1173.5  644.48  1183.5  647.57  1223.2  654.89
  1292.8  662.01  1342.6  671.99  1412.2   682.8  1471.9  689.27  1541.5  699.46
#Mann= 3 , 0 , 0
       0      .1       0  1063.2    .045       0  1078.2      .1       0
Bank Sta=1063.2,1078.2
XS Rating Curve= 0 ,0
Exp/Cntr=0.3,0.1

Type RM Length L Ch R = 1 ,3606.6  ,389.4,396.5,403.8
XS GIS Cut Line= 2
     2168240.386      365208.263     2167449.238      364106.313
#Sta/Elev= 30
     9.9  694.74    29.7  687.73      99  670.35   168.3  639.06   188.1   634.3
   217.8  622.57   247.5  616.17   376.3  605.41   485.2  601.47     604  599.42
   653.5  595.34   673.3  598.25   691.1  595.12     703   594.9   706.1  595.24
   712.9  595.99   722.8  599.84   752.5  614.18   772.3  625.07   792.1  639.38
     802  643.59   821.8  649.42   851.6  652.81  1019.9  655.54  1049.6  657.05
  1099.1  671.81  1138.7  676.09  1277.3  700.56  1326.8   710.1  1356.5  718.29
#Mann= 3 , 0 , 0
       0      .1       0   691.1    .045       0   706.1      .1       0
Bank Sta=691.1,706.1
XS Rating Curve= 0 ,0
Exp/Cntr=0.3,0.1

Type RM Length L Ch R = 1 ,3210.1  ,857.8,871,885.1
XS GIS Cut Line= 3
      2168328.37      365287.579     2168067.666      364137.082
     2167800.035      363863.469
#Sta/Elev= 30
     9.9  722.61    29.7  717.98    59.5   707.9    69.4  707.47    79.3  704.41
   148.7  674.74   168.5  670.62     228  644.29   247.8   640.3   307.3   616.9
   327.1  611.99   416.4  605.29     575  597.96   674.1  596.36   832.7  597.21
   872.7  594.17   882.3  593.04   887.7   593.6     912  599.47   971.5  603.84
   981.4  607.44    1031  631.47  1040.9  631.89  1050.8  635.39  1090.4  637.41
  1238.5  636.94  1307.2   658.8  1405.4  670.83  1523.2  689.94  1562.4  694.27
#Mann= 3 , 0 , 0
       0      .1       0   872.7    .045       0   887.7      .1       0
Bank Sta=872.7,887.7
XS Rating Curve= 0 ,0
Exp/Cntr=0.3,0.1

Type RM Length L Ch R = 1 ,2339.1  ,486.2,471.7,455.6
XS GIS Cut Line= 2
     2168946.125      365168.562     2168554.942       363883.88
#Sta/Elev= 30
     9.9     661    49.7  654.51    69.6  651.98    89.5   650.6   149.2  643.62
   218.8  637.43   248.7  633.23   268.6  631.64   298.4  627.26   328.3  621.63
   348.2  619.31     388  610.73   427.7  603.61   586.9  594.96   636.6  589.87
   642.5  589.93   657.5  590.62   696.3  593.01   925.1  598.95  1024.6  606.96
  1084.3  609.58  1094.2  610.74  1104.2  614.76    1134  638.62    1144  645.89
  1153.9  646.97  1163.9  649.88  1173.8  651.37  1223.5  655.44  1342.9  659.54
#Mann= 3 , 0 , 0
       0      .1       0   642.5    .045       0   657.5      .1       0
Bank Sta=642.5,657.5
XS Rating Curve= 0 ,0
Exp/Cntr=0.3,0.1

Type RM Length L Ch R = 1 ,1867.4  ,1840.8,1867.4,1893.1
XS GIS Cut Line= 4
     2169321.547      365045.263     2169279.552      364640.588
     2168974.137      364003.034     2168808.058       363883.88
#Sta/Elev= 30
     9.9  668.14   148.8  664.52   218.3  647.62   228.2  645.58   238.2   645.2
     258  640.84   317.5  624.66   327.5   624.5   347.3  618.82   406.8   597.7
   416.8  598.11   436.7  593.29   446.7  592.19   725.5   592.6   741.6  591.03
   756.6  588.58   765.3  588.24   795.2  592.14   924.6  597.11   964.4  601.62
  1093.9  605.42  1103.8   606.9  1113.8  609.97  1152.7  624.78  1162.4  629.46
  1181.9  633.16  1201.4   640.4  1211.1  642.65  1259.8  651.21  1318.2  656.34
#Mann= 3 , 0 , 0
       0      .1       0   741.6    .045       0   756.6      .1       0
Bank Sta=741.6,756.6
XS Rating Curve= 0 ,0
Exp/Cntr=0.3,0.1

Chan Stop Cuts=-1
Use User Specified Reach Order=0